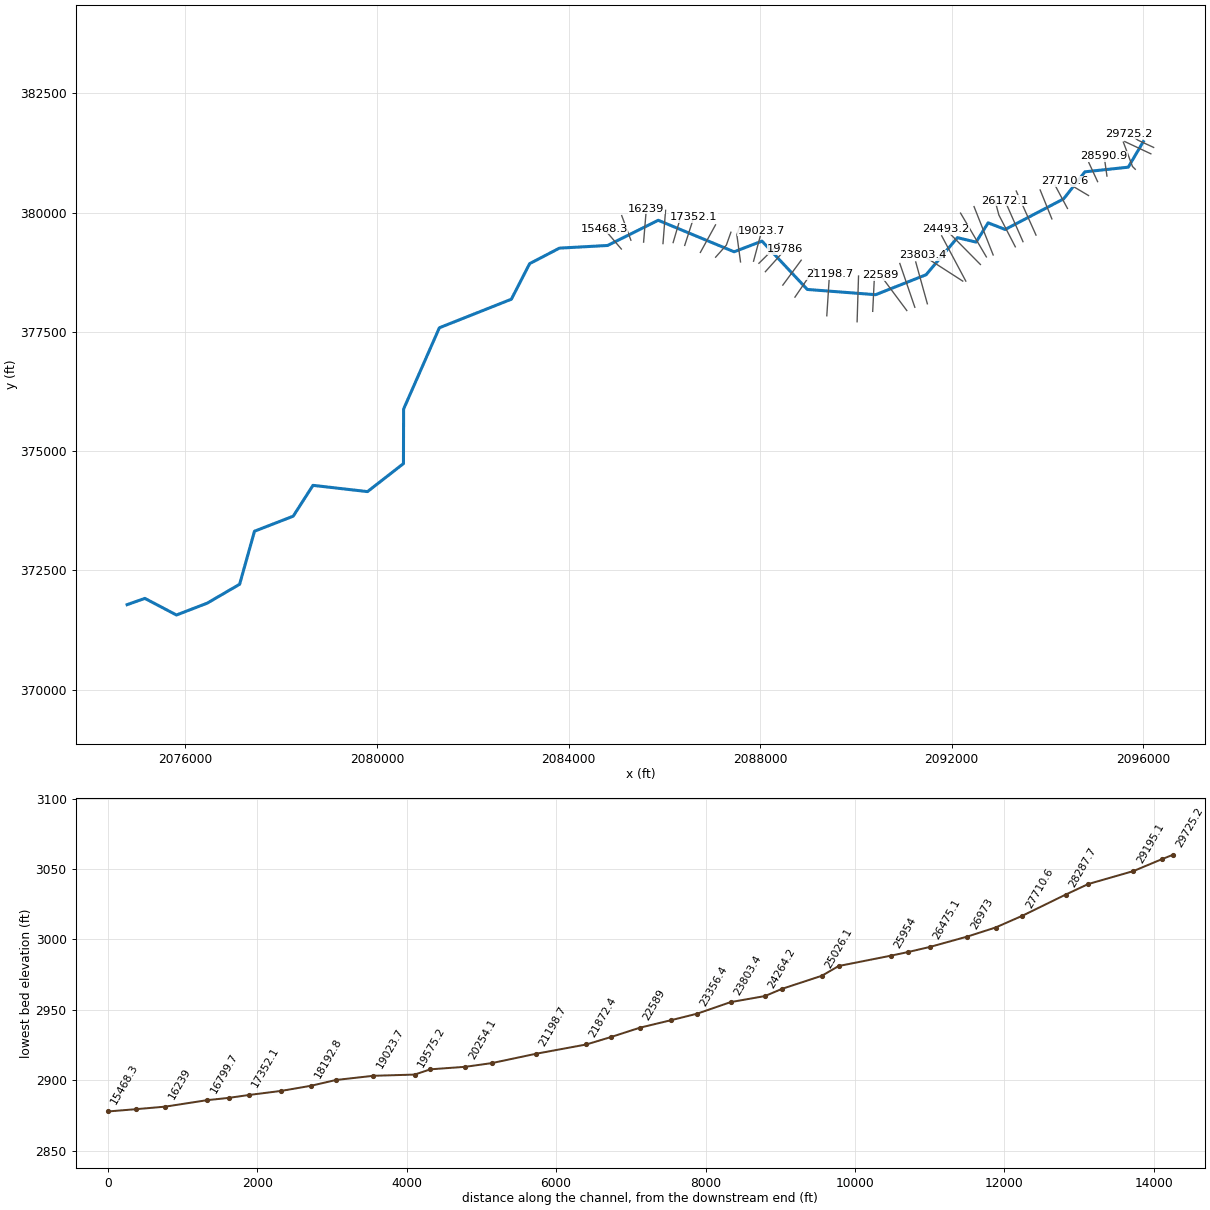
--- SFkBigClCk.prj (project) ---

Proj Title=SFkBigClCk
Current Plan=p01
Default Exp/Contr=0,0
English Units
Geom File=g01
Flow File=f01
Plan File=p01
BEGIN DESCRIPTION:
END DESCRIPTION:
DSS Export Rating Curves= 0
DSS Export Rating Curve Sorted= 0
DSS Export Volume Flow Curves= 0
DXF OffsetX= 0
DXF OffsetY= 0
DXF ScaleX= 0
DXF ScaleY= 0

--- SFkBigClCk.p01 (plan) ---

Plan Title=Floodplain
Program Version=4.00
Geom File=g01
Flow File=f01
K Sum by GR=0
Std Step Tol=0.01
Critical Tol=0.01
Num of Std Step Trials=20
Max Error Tol=0.3
Flow Tol Ratio=0.001
Split Flow NTrial=30
Split Flow Tol=0.02
Split Flow Ratio=0.02
Log Output Level=0
Friction Slope Method=1
Unsteady Friction Slope Method=2
Unsteady Bridges Friction Slope Method=1
Global Log Level=0
CheckData=False
Run HTab=0
Run UNet=0
Run PostProcess=0
UNET Theta=0
UNET Theta Warmup=0
UNET ZTol=0
UNET ZSATol=0
UNET MxIter=0
UNET MaxInSteps=0
UNET DtIC=0
UNET DtMin=0
UNET MaxCRTS=0
UNET WFStab=0
UNET SFStab=0
UNET WFX=0
UNET SFX=0
UNET DSS MLevel=0
UNET DZMax Abort=0
UNET Convert EG Bridges=0
UNET Use Existing IB Tables=0
UNET Froude Limit=0
UNET Froude Power=0
Write IC File=0
Echo Input=False
Echo Output=False
Write Detailed=0

--- SFkBigClCk.f01 (steady flow) ---

Flow Title=NFF Regression Equation
Program Version=4.00
Number of Profiles= 1
Profile Names=P100yr
River Rch & RM=SFkBigClCk,Main            ,29725.2
  1625.3
River Rch & RM=SFkBigClCk,Main            ,28590.9
 1699.46
River Rch & RM=SFkBigClCk,Main            ,24264.2
1818.266
River Rch & RM=SFkBigClCk,Main            ,17792.8
2018.003
River Rch & RM=SFkBigClCk,Main            ,17352.1
2419.085
River Rch & RM=SFkBigClCk,Main            ,12056.9
2582.286
River Rch & RM=SFkBigClCk,Main            ,7663.3
2868.984
River Rch & RM=SFkBigClCk,Main            ,260.2
3099.865
Boundary for River Rch & Prof#=SFkBigClCk,Main            , 1
Up Type= 0
Dn Type= 3
Dn Slope=0.020204
DSS Import GetInterval= 0
DSS Import GetPeak= 0
DSS Import FillOption= 0

--- SFkBigClCk.g01 (geometry) ---

Geom Title=USGS 10m DEM
Program Version=4.00

River Reach=SFkBigClCk      ,Main
Reach XY= 30
     2096001.021      381489.309     2095686.711      380953.244
     2094780.985      380855.712     2094335.978       380288.17
     2093116.386      379647.524     2092760.386      379786.198
     2092508.609      379382.403     2092119.066       379475.83
     2091464.135      378698.163     2090412.043      378280.281
     2088984.389      378390.043     2088038.363      379402.989
     2087455.632      379179.714     2085871.708      379840.033
     2084813.639      379311.769     2083808.341      379256.325
     2083186.492      378931.103     2082804.866      378185.271
      2081301.66       377587.15     2080554.617      375882.957
     2080551.533      374739.555     2079800.278      374152.501
     2078662.204      374283.817     2078249.287      373637.449
     2077440.963       373322.29     2077130.634       372210.58
     2076454.632      371815.072     2075812.091      371566.204
     2075151.768      371914.576     2074781.227      371783.144

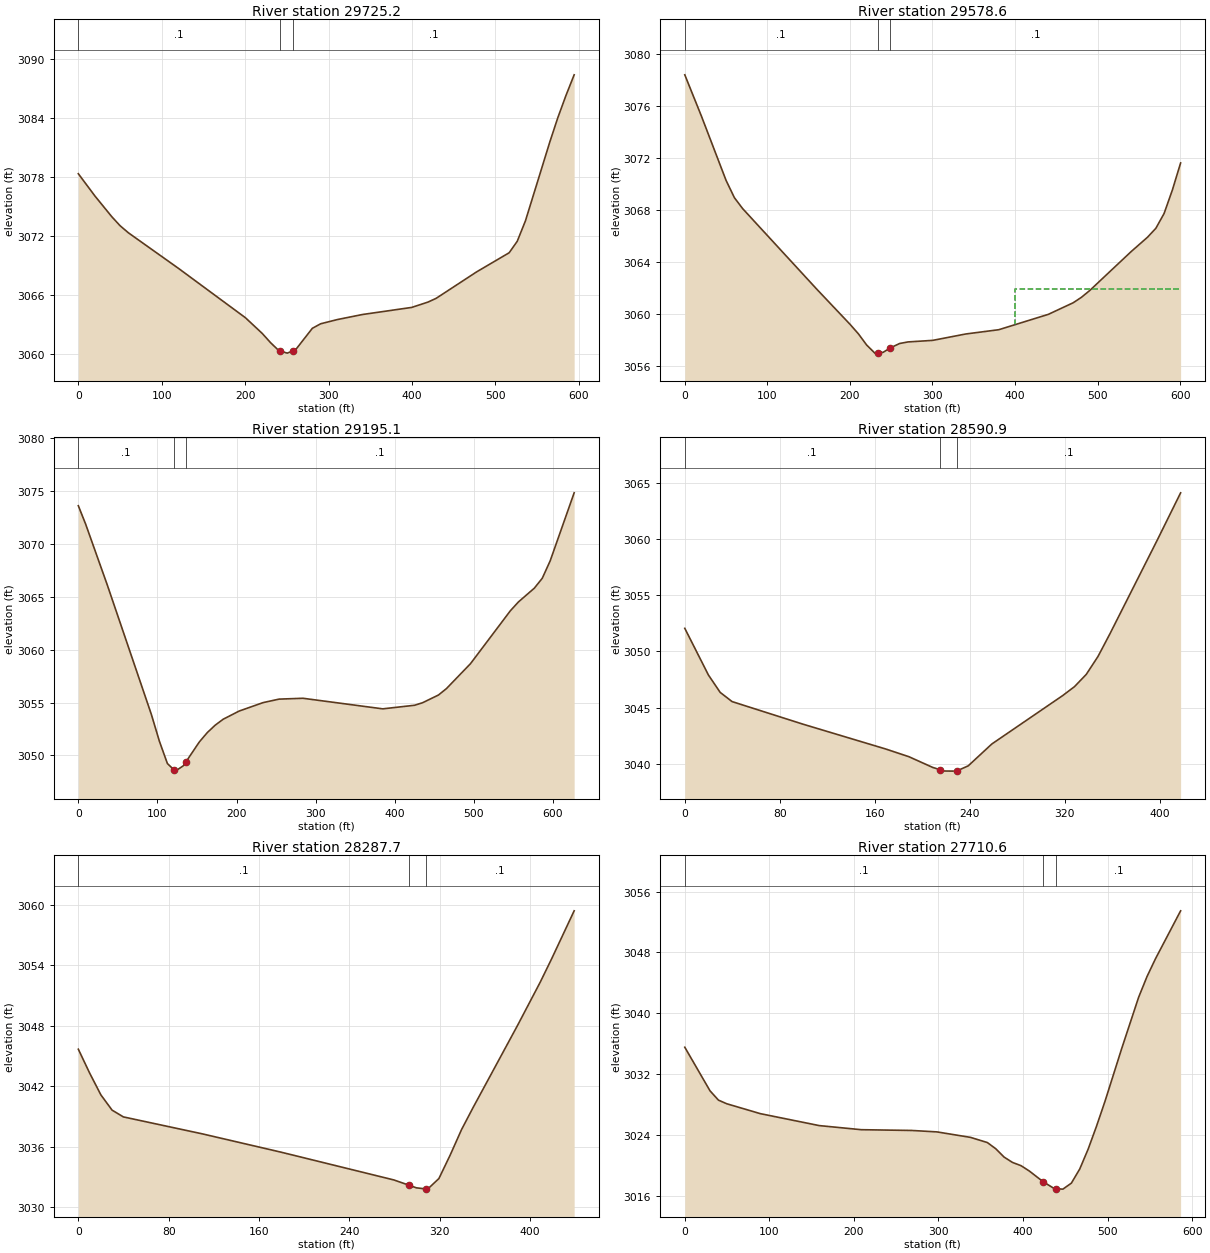
Type RM Length L Ch R = 1 ,29725.2 ,146.8,146.6,146.4
XS GIS Cut Line= 3
     2096216.531      381367.096     2095889.183      381518.781
     2095701.631      381658.243
#Sta/Elev= 29
       0 3078.31      20 3076.04    40.1 3073.95    50.1 3073.03    60.1 3072.31
   120.3 3068.69   200.4 3063.69   220.5  3062.1   230.5 3061.16   240.5 3060.35
   241.9 3060.32   250.5  3060.1   256.9 3060.32   260.6 3060.45   280.6 3062.62
   290.6 3063.08   310.7 3063.51   340.7 3064.02   399.7 3064.74   419.2 3065.28
     429 3065.66   477.6 3068.35   516.6 3070.29   526.3 3071.46   536.1 3073.53
   565.3 3081.53     575 3084.02   584.8 3086.28   594.5 3088.35
#Mann= 3 , 0 , 0
       0      .1       0   241.9    .045       0   256.9      .1       0
Bank Sta=241.9,256.9
XS Rating Curve= 0 ,0
Exp/Cntr=0.3,0.1

Type RM Length L Ch R = 1 ,29578.6 ,401.2,383.5,365.2
XS GIS Cut Line= 2
     2096158.111      381233.315     2095614.898      381489.492
#Sta/Elev= 28
       0 3078.39      20 3075.24      50 3070.28    60.1 3068.95    70.1 3068.11
   160.2  3061.9   200.2 3059.22   210.2  3058.5   220.2 3057.64   230.2 3057.01
   233.6 3057.03   240.2 3057.07   248.6  3057.4   260.2 3057.75   270.3 3057.87
   300.3 3057.99   340.3 3058.48   380.4 3058.81   440.4 3059.99   470.5 3060.88
   480.5  3061.3   490.5 3061.82   540.5  3064.8   560.6 3065.92   570.6  3066.6
   580.6 3067.74   590.6 3069.54   600.6 3071.62
#Mann= 3 , 0 , 0
       0      .1       0   233.6    .045       0   248.6      .1       0
#XS Ineff= 2 , 0
       0                  399.91       0 3061.91
Permanent Ineff=
       F       F
Bank Sta=233.6,248.6
XS Rating Curve= 0 ,0
Exp/Cntr=0.3,0.1

Type RM Length L Ch R = 1 ,29195.1 ,608.6,604.2,600.5
XS GIS Cut Line= 3
     2095832.618      380909.213     2095774.479      380967.503
     2095584.063       381477.69
#Sta/Elev= 30
       0 3073.61     9.2 3071.88    36.6 3066.12    92.4 3053.86   102.5 3051.34
   112.6 3049.23   121.1 3048.62   122.7 3048.51   132.8 3049.02   136.1 3049.39
   152.9 3051.26     163 3052.15   173.1 3052.86   183.2 3053.42   203.3 3054.19
   233.6 3054.99   253.8 3055.32     284  3055.4   384.9  3054.4   425.2 3054.74
   435.3 3054.98   455.4 3055.71   465.5 3056.32   495.8 3058.67   546.2 3063.67
   556.3  3064.5   576.5 3065.81   586.6 3066.75   596.6  3068.4   626.9 3074.83
#Mann= 3 , 0 , 0
       0      .1       0   121.1    .045       0   136.1      .1       0
Bank Sta=121.1,136.1
XS Rating Curve= 0 ,0
Exp/Cntr=0.3,0.1

Type RM Length L Ch R = 1 ,28590.9 ,296.4,303.2,310
XS GIS Cut Line= 2
     2095241.386      380766.502     2095183.137      381180.072
#Sta/Elev= 21
       0 3052.06    19.9  3047.9    29.8 3046.35    39.8 3045.53    99.4 3043.52
     169 3041.31   188.9 3040.61   208.8 3039.66   214.6 3039.47   218.8 3039.34
   228.7 3039.33   229.6 3039.37   238.7  3039.8   258.6 3041.75   318.2 3046.06
   328.2 3046.86   338.1 3047.95     348 3049.55     358 3051.56   397.8  3059.9
   417.6 3064.14
#Mann= 3 , 0 , 0
       0      .1       0   214.6    .045       0   229.6      .1       0
Bank Sta=214.6,229.6
XS Rating Curve= 0 ,0
Exp/Cntr=0.3,0.1

Type RM Length L Ch R = 1 ,28287.7 ,563.6,577.1,590.6
XS GIS Cut Line= 2
     2095046.251      380650.003     2094862.765      381049.011
#Sta/Elev= 20
       0 3045.67      10 3043.31      20 3041.14    29.9 3039.63    39.9 3038.96
   109.8 3037.28   179.7 3035.46   279.5 3032.71   292.6  3032.2   299.4 3031.93
   307.6 3031.82   309.4  3031.8   319.4 3032.85   329.4 3035.18   339.4 3037.69
   349.3 3039.81   389.3 3048.08   409.2 3052.33   419.2 3054.62   439.2 3059.39
#Mann= 3 , 0 , 0
       0      .1       0   292.6    .045       0   307.6      .1       0
Bank Sta=292.6,307.6
XS Rating Curve= 0 ,0
Exp/Cntr=0.3,0.1

Type RM Length L Ch R = 1 ,27710.6 ,373.2,360.4,347.7
XS GIS Cut Line= 2
      2094856.94      380358.756     2094353.083       380658.74
#Sta/Elev= 30
       0 3035.52    29.8 3029.79    39.8 3028.56    49.7 3028.08    89.4 3026.78
     159 3025.21   208.7 3024.67   268.4 3024.57   298.2 3024.38   337.9 3023.66
   357.8 3022.98   367.7 3022.17   377.7 3021.06   387.6 3020.36   397.6 3019.94
   407.5 3019.23   424.1  3017.8   437.3  3016.9   439.1 3016.89   447.2 3016.85
   457.2 3017.64   467.1  3019.5   477.1 3022.13     487 3025.15     497 3028.42
   516.8 3035.38   536.7 3042.08   546.6 3044.81   556.6 3047.15   586.4 3053.47
#Mann= 3 , 0 , 0
       0      .1       0   424.1    .045       0   439.1      .1       0
Bank Sta=424.1,439.1
XS Rating Curve= 0 ,0
Exp/Cntr=0.3,0.1

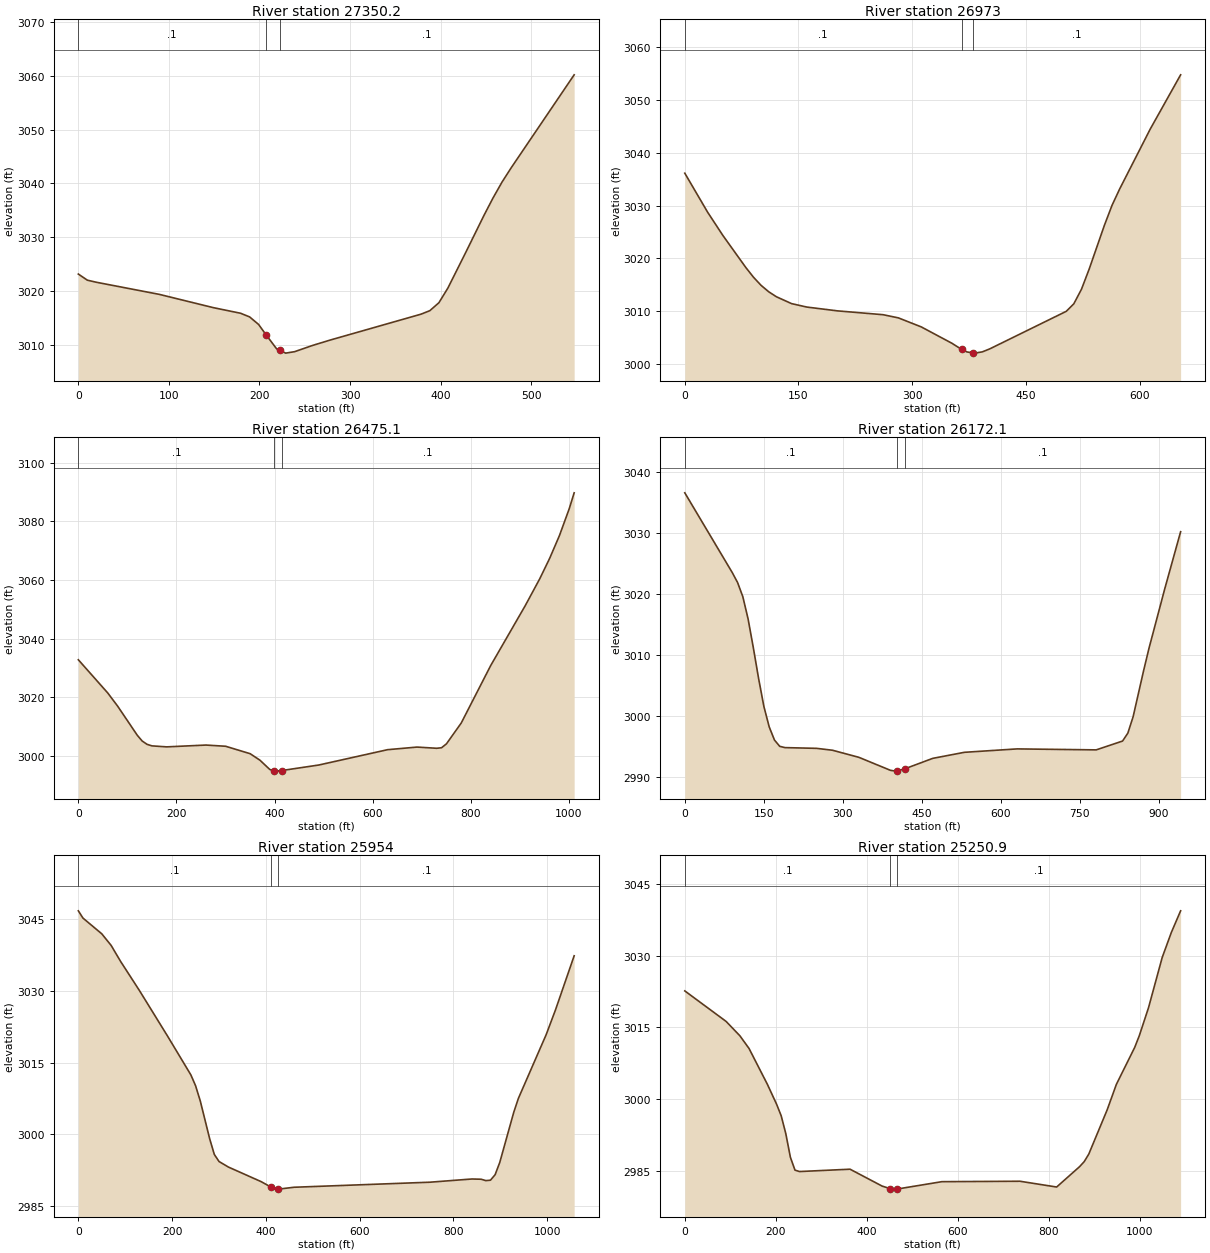
Type RM Length L Ch R = 1 ,27350.2 ,379.6,377.2,374.7
XS GIS Cut Line= 2
     2094416.861      380088.458      2094158.78      380571.171
#Sta/Elev= 25
       0 3023.16      10 3022.02    19.9 3021.64    89.6 3019.38   149.3 3016.91
   179.1 3015.88   189.1  3015.2     199  3013.8   207.1 3011.91     219 3009.25
   222.1 3009.01   228.9 3008.47   238.8 3008.74   258.8 3009.91   278.7 3010.93
   378.2  3015.7   388.1 3016.36   398.1 3017.84     408 3020.56     428 3027.28
   447.8 3034.05   457.8 3037.29   467.8 3040.26   477.7 3042.86   547.4 3060.18
#Mann= 3 , 0 , 0
       0      .1       0   207.1    .045       0   222.1      .1       0
Bank Sta=207.1,222.1
XS Rating Curve= 0 ,0
Exp/Cntr=0.3,0.1

Type RM Length L Ch R = 1 ,26973   ,497.3,497.9,498.5
XS GIS Cut Line= 2
     2094091.226      379868.739      2093846.85      380475.628
#Sta/Elev= 30
       0 3036.15    30.2 3028.74    50.3 3024.34    80.5 3018.28    90.6 3016.44
   100.6  3014.9   110.7 3013.68   120.8 3012.74   140.9 3011.43     161 3010.78
   201.3 3010.06   261.7 3009.33   281.8 3008.73     312 3007.02   352.3 3003.93
   365.1 3002.77   372.4 3002.27   380.1  3002.1   382.5 3002.05   392.6 3002.29
   402.6 3002.87   503.3 3009.97   513.3  3011.4   523.4 3014.16   533.5 3017.96
   553.6 3026.26   563.7 3030.06   573.7 3033.14     614 3044.48   654.2 3054.79
#Mann= 3 , 0 , 0
       0      .1       0   365.1    .045       0   380.1      .1       0
Bank Sta=365.1,380.1
XS Rating Curve= 0 ,0
Exp/Cntr=0.3,0.1

Type RM Length L Ch R = 1 ,26475.1 ,303.1,302.9,302.8
XS GIS Cut Line= 2
     2093760.043      379529.388     2093347.525      380452.248
#Sta/Elev= 30
       0 3032.75      60 3021.41    80.1 3016.93   120.1    3007   130.1 3005.02
   140.1 3003.88   150.1 3003.35   180.2 3003.01   260.2 3003.63   300.3 3003.22
   350.3 3000.68   370.3 2998.46   390.3  2995.3   399.4 2994.79   400.3 2994.73
   414.4 2994.92   490.4 2996.82   630.5 3002.05   690.6 3002.94   730.6 3002.53
   740.6 3002.71   750.6 3004.06   780.7 3011.16   840.7 3030.76   910.8 3051.11
   940.8 3060.41   960.8 3067.32   980.8  3075.1  1000.8 3084.28  1010.9 3089.74
#Mann= 3 , 0 , 0
       0      .1       0   399.4    .045       0   414.4      .1       0
Bank Sta=399.4,414.4
XS Rating Curve= 0 ,0
Exp/Cntr=0.3,0.1

Type RM Length L Ch R = 1 ,26172.1 ,216.7,218.1,219.5
XS GIS Cut Line= 2
      2093488.08      379391.816     2093109.459      380253.907
#Sta/Elev= 30
       0 3036.56    90.2 3023.49   100.2 3021.88   110.2 3019.55   120.2 3015.91
   130.2 3011.17   140.2 3006.13   150.2 3001.57   160.3 2998.22   170.3 2996.07
   180.3 2995.04   190.3 2994.83   250.4 2994.71   280.5  2994.4   330.6 2993.24
   390.6 2991.11   400.7 2990.98   403.5 2991.02   418.5 2991.38   470.8 2993.07
   530.9 2994.06     631 2994.62   781.3 2994.46   831.4 2995.91   841.4 2997.21
   851.4 2999.89   871.4 3007.47   881.5 3011.09   911.5 3020.85   941.6 3030.19
#Mann= 3 , 0 , 0
       0      .1       0   403.5    .045       0   418.5      .1       0
Bank Sta=403.5,418.5
XS Rating Curve= 0 ,0
Exp/Cntr=0.3,0.1

Type RM Length L Ch R = 1 ,25954   ,705.3,703.2,699.6
XS GIS Cut Line= 3
     2093327.894      379284.055     2092984.348      379950.993
     2092905.586      380248.082
#Sta/Elev= 30
       0 3046.78      10 3045.25      50 3041.97      70 3039.54      90 3036.22
     130 3030.15   190.1  3020.6   240.1 3012.44   250.1 3010.17   260.1    3007
   280.1  2999.1   290.1 2995.79   300.1 2994.32   320.1 2993.16   390.1  2990.1
   411.9 2988.91   426.9 2988.54   460.1 2988.93   750.2 2989.99   839.4 2990.66
   859.3 2990.61   869.2 2990.32   879.1 2990.41     889 2991.56   898.9 2994.12
   928.7  3004.6   938.6 3007.52   998.1 3020.91  1017.9 3026.08  1057.6 3037.37
#Mann= 3 , 0 , 0
       0      .1       0   411.9    .045       0   426.9      .1       0
Bank Sta=411.9,426.9
XS Rating Curve= 0 ,0
Exp/Cntr=0.3,0.1

Type RM Length L Ch R = 1 ,25250.9 ,220.7,224.7,230.1
XS GIS Cut Line= 2
     2092865.448      379113.134     2092466.233      380126.743
#Sta/Elev= 30
       0 3022.64    90.8 3016.25     121 3013.25   141.2 3010.58   181.6 3003.06
   201.7 2998.92   211.8  2996.5   221.9 2992.78     232 2987.82   242.1 2985.12
   252.2 2984.83   363.1 2985.32   433.7 2981.78   451.7 2981.24     464 2981.15
   466.7 2981.17   564.9 2982.71   736.4  2982.8     817 2981.59   867.5 2985.86
   877.6 2986.91   887.6 2988.48     928 2997.74   948.2 3003.07   988.5 3010.81
   998.6 3013.26  1018.8  3019.1    1049 3029.66  1069.2 3034.92  1089.4  3039.4
#Mann= 3 , 0 , 0
       0      .1       0   451.7    .045       0   466.7      .1       0
Bank Sta=451.7,466.7
XS Rating Curve= 0 ,0
Exp/Cntr=0.3,0.1

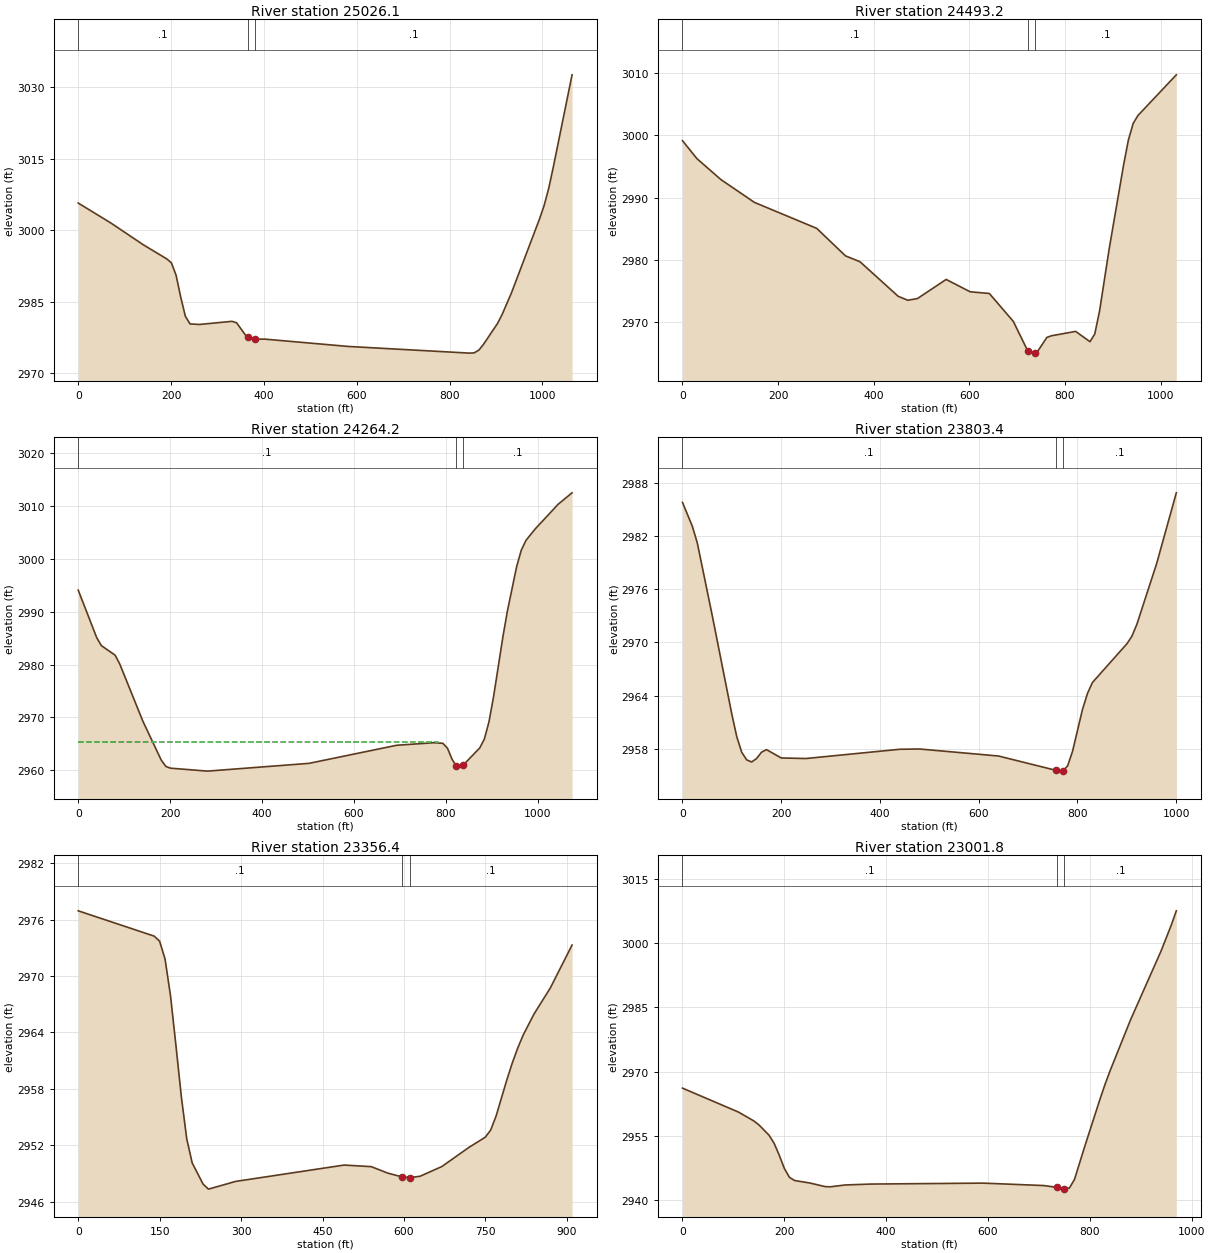
Type RM Length L Ch R = 1 ,25026.1 ,526.9,532.9,538.9
XS GIS Cut Line= 2
     2092723.334       379072.53     2092184.691      379989.978
#Sta/Elev= 30
       0 3005.73    70.3 3001.55   140.5 2996.96   190.7 2994.02   200.7  2993.2
   210.8  2990.6   220.8 2986.01   230.8 2981.98   240.9 2980.38     261 2980.26
   331.2 2980.92   341.2 2980.61   361.3  2977.9   365.1 2977.62   371.4 2977.16
   380.1 2977.16   401.5 2977.19   582.1 2975.65   843.1 2974.25   853.1 2974.31
   863.2 2974.89   873.2 2976.11   903.3 2980.47   913.3 2982.37   933.4  2986.9
   993.6 3002.34  1003.7  3005.2  1013.7 3008.85  1023.7 3013.37  1063.9 3032.63
#Mann= 3 , 0 , 0
       0      .1       0   365.1    .045       0   380.1      .1       0
Bank Sta=365.1,380.1
XS Rating Curve= 0 ,0
Exp/Cntr=0.3,0.1

Type RM Length L Ch R = 1 ,24493.2 ,235.7,229,222.4
XS GIS Cut Line= 2
     2092599.411      378913.087     2091874.451      379648.535
#Sta/Elev= 30
       0 2999.16    30.1 2996.28    80.2 2992.91   150.4 2989.23   280.7 2985.05
   340.9 2980.62     371 2979.69   451.2 2974.11   471.2 2973.48   491.3 2973.75
   551.4 2976.83   601.6 2974.84   641.7 2974.57   691.8 2970.08   721.7 2965.38
   731.9 2964.97   736.7 2965.06   741.9 2965.16     762  2967.5     772 2967.77
   822.1 2968.47   852.2 2966.81   862.2 2968.06   872.3  2971.8   892.3 2981.75
   922.4 2995.24   932.4 2999.25   942.5 3001.94   952.5 3003.22  1032.7 3009.76
#Mann= 3 , 0 , 0
       0      .1       0   721.7    .045       0   736.7      .1       0
Bank Sta=721.7,736.7
XS Rating Curve= 0 ,0
Exp/Cntr=0.3,0.1

Type RM Length L Ch R = 1 ,24264.2 ,450.1,460.8,471.9
XS GIS Cut Line= 2
      2092294.09      378564.978     2091790.422       379514.01
#Sta/Elev= 30
       0 2994.08    40.2 2985.09    50.2 2983.59    80.3 2981.77    90.4  2980.1
   140.6 2969.29   180.7 2961.91   190.8 2960.72   200.8  2960.4   281.2 2959.84
   502.1 2961.31   692.8 2964.73   773.2 2965.21   793.2 2965.11   803.3 2964.18
   813.3  2962.1   822.1 2960.83   837.1 2960.94   873.6 2964.23   883.6 2965.91
   893.7 2969.18   903.7 2973.95   923.8 2985.17   933.8 2990.15   953.9 2998.55
     964 3001.65     974 3003.47   994.1 3005.64  1044.3 3010.33  1074.4 3012.48
#Mann= 3 , 0 , 0
       0      .1       0   822.1    .045       0   837.1      .1       0
#XS Ineff= 2 , 0
          783.35 2965.29
Permanent Ineff=
       F       F
Bank Sta=822.1,837.1
XS Rating Curve= 0 ,0
Exp/Cntr=0.3,0.1

Type RM Length L Ch R = 1 ,23803.4 ,463.9,447,430.2
XS GIS Cut Line= 2
     2092230.284      378564.978     2091390.188      379108.193
#Sta/Elev= 30
       0 2985.76      20 2983.07      30  2981.2      60  2973.1     100 2961.91
     110 2959.39     120 2957.64     130 2956.79   140.1 2956.55   150.1 2956.94
   160.1 2957.65   170.1 2957.94   200.1    2957   250.1 2956.94   440.2 2957.98
   480.2 2958.01   640.3 2957.22   756.5 2955.61   770.3 2955.52   771.5 2955.59
   780.3 2956.12   790.3 2957.78   810.3 2962.46   820.4 2964.26   830.4 2965.49
   900.4 2969.86   910.4  2970.7   920.4 2972.03   960.4 2978.85  1000.4 2986.84
#Mann= 3 , 0 , 0
       0      .1       0   756.5    .045       0   771.5      .1       0
Bank Sta=756.5,771.5
XS Rating Curve= 0 ,0
Exp/Cntr=0.3,0.1

Type RM Length L Ch R = 1 ,23356.4 ,353.5,354.6,355.7
XS GIS Cut Line= 2
     2091491.078      378089.561     2091248.632      378966.275
#Sta/Elev= 30
       0 2976.93   139.9 2974.24   149.9  2973.7   159.9 2971.81   169.9 2967.94
   179.9 2962.66   189.9 2957.17   199.9 2952.67   209.9 2950.12   229.9 2947.87
   239.9 2947.33   289.9 2948.15   489.8 2949.89   539.8 2949.72   569.8 2949.04
   595.7 2948.64   610.7 2948.55   629.7  2948.7   669.7 2949.73   719.7 2951.77
   749.7 2952.85   759.7 2953.61   769.7 2955.11   789.7 2958.99   799.7 2960.78
   809.7 2962.36   819.7 2963.73   839.6 2965.96   869.6 2968.73   909.6 2973.29
#Mann= 3 , 0 , 0
       0      .1       0   595.7    .045       0   610.7      .1       0
Bank Sta=595.7,610.7
XS Rating Curve= 0 ,0
Exp/Cntr=0.3,0.1

Type RM Length L Ch R = 1 ,23001.8 ,406.1,412.7,419.4
XS GIS Cut Line= 2
     2091229.768      378016.645     2090916.521       378934.58
#Sta/Elev= 30
       0 2966.17     110 2960.59     140 2958.54     150 2957.62     170 2955.21
     180 2953.31     190 2950.56     200 2947.47     210  2945.4     220 2944.65
     250 2944.07     280 2943.23     290 2943.18     320 2943.61     370 2943.82
     590 2944.04   709.9 2943.47   735.2 2943.06   749.9 2942.64   750.2 2942.64
   759.9 2942.89   769.9  2944.9   789.9 2952.54   819.9 2963.57   829.9 2967.05
   839.9 2970.24   879.9 2982.06   939.9 2998.11   959.9 3004.13   969.9 3007.48
#Mann= 3 , 0 , 0
       0      .1       0   735.2    .045       0   750.2      .1       0
Bank Sta=735.2,750.2
XS Rating Curve= 0 ,0
Exp/Cntr=0.3,0.1

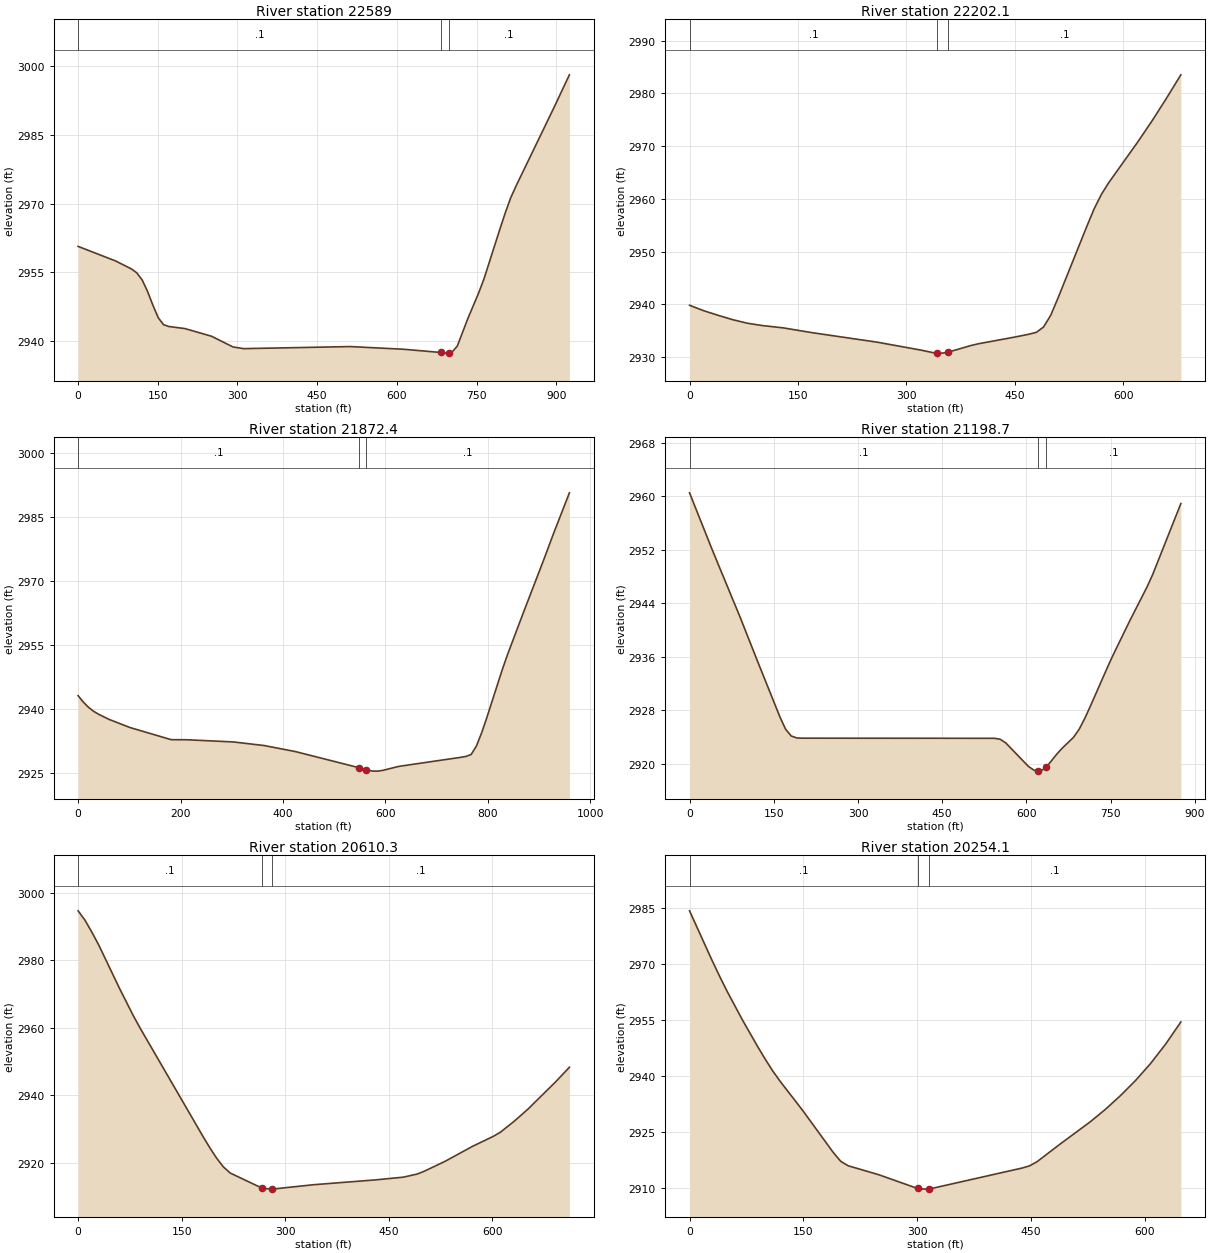
Type RM Length L Ch R = 1 ,22589   ,402.6,386.9,371.2
XS GIS Cut Line= 2
     2091061.784      377948.245     2090510.705      378690.947
#Sta/Elev= 30
       0 2960.67    70.4  2957.5   100.5 2955.74   110.6 2954.88   120.6 2953.34
   130.7 2950.84   140.7 2947.86   150.8 2945.11   160.8 2943.58   170.9 2943.18
     201 2942.73   251.3 2941.05   291.5 2938.72   311.6 2938.35   512.7  2938.8
   613.2 2938.21   682.8 2937.51   693.6 2937.37   697.8 2937.45   703.7 2937.57
   713.7  2938.9   733.8 2944.96   753.9 2950.49     764 2953.57   794.1 2964.49
   804.2 2968.03   814.2 2971.24   824.3 2973.84   894.7 2990.72   924.8 2998.12
#Mann= 3 , 0 , 0
       0      .1       0   682.8    .045       0   697.8      .1       0
Bank Sta=682.8,697.8
XS Rating Curve= 0 ,0
Exp/Cntr=0.3,0.1

Type RM Length L Ch R = 1 ,22202.1 ,329.3,329.7,330.1
XS GIS Cut Line= 2
     2090350.171      377931.127     2090383.303      378610.177
#Sta/Elev= 30
       0 2939.81      20 2938.76      40 2937.89      60 2937.07      80 2936.41
     100 2935.98     130 2935.52     170 2934.61     260 2932.81   319.9 2931.32
   339.9 2930.75     343 2930.75   349.9 2930.74     358 2930.93   389.9  2932.2
   399.9 2932.52   449.9 2933.78   469.9 2934.33   479.9 2934.68   489.9 2935.69
   499.9 2937.93   509.9 2941.18   549.9 2954.81   559.9 2958.09   569.9 2960.82
   579.9 2963.01   619.9  2970.7   639.9 2974.74   659.9 2979.03   679.9  2983.5
#Mann= 3 , 0 , 0
       0      .1       0     343    .045       0     358      .1       0
Bank Sta=343,358
XS Rating Curve= 0 ,0
Exp/Cntr=0.3,0.1

Type RM Length L Ch R = 1 ,21872.4 ,675.2,673.8,672.4
XS GIS Cut Line= 2
     2090024.304      377712.589     2090054.133      378671.116
#Sta/Elev= 30
       0 2943.17    10.1 2941.68    20.2 2940.46    30.3 2939.51    40.4 2938.78
    60.6  2937.6     101 2935.71   181.7 2932.85     212 2932.83   302.8 2932.32
   363.4 2931.47     424 2930.06   547.8 2926.29   562.8 2925.78   575.4 2925.47
   585.5 2925.47   595.6 2925.67   625.9 2926.58     747 2928.71   757.1 2928.92
   767.2 2929.38   777.3 2931.31   787.4 2934.37   797.5  2937.9   827.8 2949.22
   837.9 2952.71   868.1 2962.32   908.5 2974.93   928.7 2981.42     959 2990.76
#Mann= 3 , 0 , 0
       0      .1       0   547.8    .045       0   562.8      .1       0
Bank Sta=547.8,562.8
XS Rating Curve= 0 ,0
Exp/Cntr=0.3,0.1

Type RM Length L Ch R = 1 ,21198.7 ,600.4,588.3,576.2
XS GIS Cut Line= 2
     2089391.618      377838.473     2089447.829       378711.68
#Sta/Elev= 30
       0 2960.51    40.2 2952.03    90.5 2941.82   120.7  2935.4   160.9    2927
     171 2925.16     181 2924.14   191.1 2923.84   201.2 2923.81   543.1 2923.79
   553.2 2923.65   563.2  2923.1   603.5 2919.59   613.5 2919.01   620.7 2918.92
   623.6 2918.88   633.6 2919.29   635.7  2919.5   653.8  2921.4   663.8 2922.32
   683.9 2923.94     694 2925.16     704 2926.78   714.1 2928.64   744.3 2934.41
   754.3 2936.24   784.5 2941.45   814.7 2946.42   824.7 2948.26     875  2958.9
#Mann= 3 , 0 , 0
       0      .1       0   620.7    .045       0   635.7      .1       0
Bank Sta=620.7,635.7
XS Rating Curve= 0 ,0
Exp/Cntr=0.3,0.1

Type RM Length L Ch R = 1 ,20610.3 ,357.1,356.2,355.3
XS GIS Cut Line= 2
     2088726.458      378229.079     2089126.774      378817.224
#Sta/Elev= 30
       0 2994.63      10 2991.85      20 2988.29    30.1 2984.43    60.1 2971.62
    80.2  2963.5    90.2 2959.79   180.4 2928.02   190.4 2924.63   200.4 2921.49
   210.4 2918.85   220.4 2917.03   260.5 2913.14   266.4 2912.75   270.6 2912.48
   280.6 2912.28   281.4 2912.29   340.7 2913.58   430.9 2915.02     471 2915.82
     491 2916.74     501 2917.55   531.1 2920.48   571.2 2924.95   601.2  2927.9
   611.2 2929.08   631.3 2932.34   651.3 2935.94   691.4 2944.02   711.4 2948.34
#Mann= 3 , 0 , 0
       0      .1       0   266.4    .045       0   281.4      .1       0
Bank Sta=266.4,281.4
XS Rating Curve= 0 ,0
Exp/Cntr=0.3,0.1

Type RM Length L Ch R = 1 ,20254.1 ,469,468.1,467.1
XS GIS Cut Line= 2
     2088473.482      378481.436     2088857.202      379003.373
#Sta/Elev= 30
       0 2984.22    29.9 2970.84    39.9 2966.58    49.8 2962.55    69.8 2954.96
    89.7 2947.88    99.7  2944.5   109.6 2941.34   119.6  2938.5   149.5 2930.64
   189.4 2919.49   199.3  2917.1   209.3 2915.89   249.2 2913.52     299 2909.94
   301.1 2909.88     309 2909.64   316.1 2909.76   318.9  2909.8   438.5 2915.29
   448.5 2915.89   458.4 2917.02   488.4 2921.68   528.2 2927.66   548.2    2931
   568.1 2934.68     588 2938.74     608 2943.33   627.9 2948.55   647.8 2954.43
#Mann= 3 , 0 , 0
       0      .1       0   301.1    .045       0   316.1      .1       0
Bank Sta=301.1,316.1
XS Rating Curve= 0 ,0
Exp/Cntr=0.3,0.1

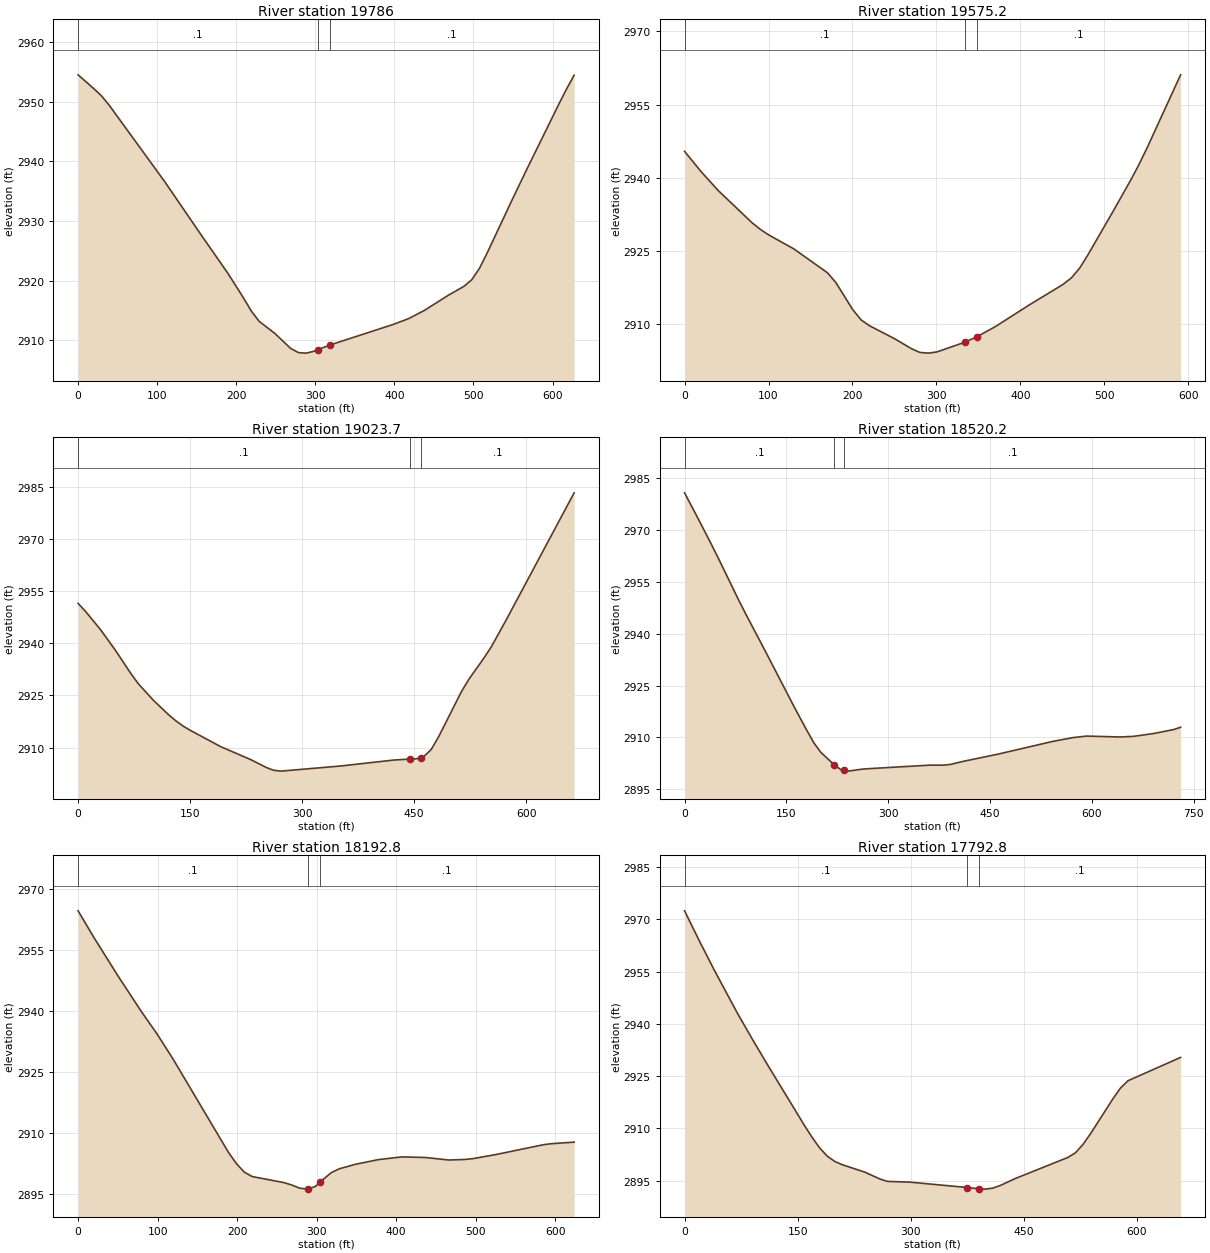
Type RM Length L Ch R = 1 ,19786   ,213.2,210.8,208.5
XS GIS Cut Line= 2
     2088108.572      378762.534     2088526.753      379230.073
#Sta/Elev= 30
       0 2954.53    19.9 2952.21    29.9 2950.96    39.8 2949.35   109.5 2936.62
   159.3 2926.97   189.2 2921.29   209.1 2917.12     219 2914.92     229 2913.18
   248.9 2911.15   268.8 2908.64   278.8 2907.93   288.7 2907.85   298.7 2908.18
   303.2 2908.43   318.2  2909.2   398.3 2912.65   418.2 2913.65   438.1 2915.03
     468 2917.54   487.9 2919.05   497.8 2920.15   507.8 2922.12   517.8 2924.78
   547.6 2933.21   567.5  2938.7   607.4 2949.46   617.3 2952.06   627.3 2954.46
#Mann= 3 , 0 , 0
       0      .1       0   303.2    .045       0   318.2      .1       0
Bank Sta=303.2,318.2
XS Rating Curve= 0 ,0
Exp/Cntr=0.3,0.1

Type RM Length L Ch R = 1 ,19575.2 ,535,551.6,558.4
XS GIS Cut Line= 2
     2087974.383      378938.751     2088393.992      379354.832
#Sta/Elev= 30
       0 2945.42      20 2941.21    40.1  2937.4    80.1 2930.85    90.1 2929.47
   100.2 2928.32   130.2 2925.45   170.3 2920.56   180.3 2918.55   200.3 2913.03
   210.3 2910.92   220.4 2909.72   250.4 2907.05   270.4 2905.02   280.4 2904.26
   290.5 2904.12   300.5 2904.36   333.5 2906.33   348.5 2907.48   370.6 2909.59
   410.6 2913.98   450.7 2918.17   460.7  2919.5   470.7 2921.53   480.8 2924.32
   510.8 2933.24   530.8 2939.33   540.8 2942.55   550.9  2946.1   590.9 2961.08
#Mann= 3 , 0 , 0
       0      .1       0   333.5    .045       0   348.5      .1       0
Bank Sta=333.5,348.5
XS Rating Curve= 0 ,0
Exp/Cntr=0.3,0.1

Type RM Length L Ch R = 1 ,19023.7 ,494.3,503.5,512.7
XS GIS Cut Line= 2
     2087861.963      378982.453     2088033.393      379624.098
#Sta/Elev= 30
       0 2951.45    10.1 2949.11    30.2 2943.86    50.3 2937.88    70.4 2931.38
    80.5  2928.4   100.6 2923.66   120.8 2919.54   130.8 2917.72   140.9 2916.16
   150.9  2914.9   191.2 2910.26   231.4 2906.55   251.6 2904.35   261.6 2903.51
   271.7 2903.26   352.2 2904.75   422.6 2906.44   443.8 2906.72   452.8  2906.8
   458.8 2907.17   462.9 2907.42     473 2909.53     483 2913.24   513.2 2926.06
   523.3 2929.67   543.4 2935.73   553.5 2939.04   573.6 2946.84   664.2  2983.2
#Mann= 3 , 0 , 0
       0      .1       0   443.8    .045       0   458.8      .1       0
Bank Sta=443.8,458.8
XS Rating Curve= 0 ,0
Exp/Cntr=0.3,0.1

Type RM Length L Ch R = 1 ,18520.2 ,347,327.4,307.9
XS GIS Cut Line= 3
     2087589.942      378967.042     2087513.431      379534.234
      2087562.99      379684.828
#Sta/Elev= 30
       0 2980.72    20.1 2973.23    40.2 2965.57    50.2 2961.64    80.3 2949.49
    90.4 2945.61   120.5 2934.38   160.6 2919.18   180.7 2911.85   190.8 2908.36
   200.8 2905.69   220.4 2902.12   230.9 2900.61   235.4 2900.45     241 2900.26
   261.1 2900.82   271.1 2900.97   361.5 2901.99   381.6 2901.98   391.6 2902.19
   411.7 2903.13   461.9 2905.17   542.2 2908.84   572.3 2909.95   592.2 2910.39
   641.7 2910.13   661.5 2910.31   691.2 2911.13     721 2912.29   730.9 2912.95
#Mann= 3 , 0 , 0
       0      .1       0   220.4    .045       0   235.4      .1       0
Bank Sta=220.4,235.4
XS Rating Curve= 0 ,0
Exp/Cntr=0.3,0.1

Type RM Length L Ch R = 1 ,18192.8 ,394.9,400,405.1
XS GIS Cut Line= 3
     2087069.947      379066.472     2087294.352      379319.795
     2087389.122      379589.142
#Sta/Elev= 30
       0 2964.67    19.9 2958.11    49.8 2948.78    79.6  2939.9    99.5 2934.34
   119.4 2928.23   189.1 2905.28   199.1 2902.51     209 2900.41     219 2899.31
   258.8 2897.83   268.8 2897.23   278.7 2896.46   288.7 2896.22   289.3 2896.26
   298.6 2896.89   304.3 2897.96   318.5 2900.28   328.5 2901.21   348.3  2902.3
   377.8 2903.48   407.3 2904.15   436.9    2904   466.4 2903.38   486.1 2903.51
     496  2903.7   525.5 2904.72   584.6 2907.11   594.4 2907.38     624 2907.78
#Mann= 3 , 0 , 0
       0      .1       0   289.3    .045       0   304.3      .1       0
Bank Sta=289.3,304.3
XS Rating Curve= 0 ,0
Exp/Cntr=0.3,0.1

Type RM Length L Ch R = 1 ,17792.8 ,436.2,440.7,445.1
XS GIS Cut Line= 2
     2086751.601      379166.512     2087067.669      379743.943
#Sta/Elev= 30
       0 2972.43      20 2963.64    39.9 2955.23    69.8 2943.19    89.8 2935.65
   109.7  2928.4   159.6 2910.66   169.6 2907.33   179.5 2904.33   189.5    2902
   199.5 2900.49   209.4 2899.56   239.4 2897.42   259.3 2895.46   269.3 2894.78
   299.2 2894.56   375.4 2893.02   390.4 2892.66     399 2892.56   408.9 2892.84
   418.9 2893.59   438.8 2895.59   508.7 2901.65   518.6 2902.96   528.6 2905.34
   538.6 2908.42   568.5 2918.48   578.5 2921.56   588.5 2923.67   658.3 2930.36
#Mann= 3 , 0 , 0
       0      .1       0   375.4    .045       0   390.4      .1       0
Bank Sta=375.4,390.4
XS Rating Curve= 0 ,0
Exp/Cntr=0.3,0.1

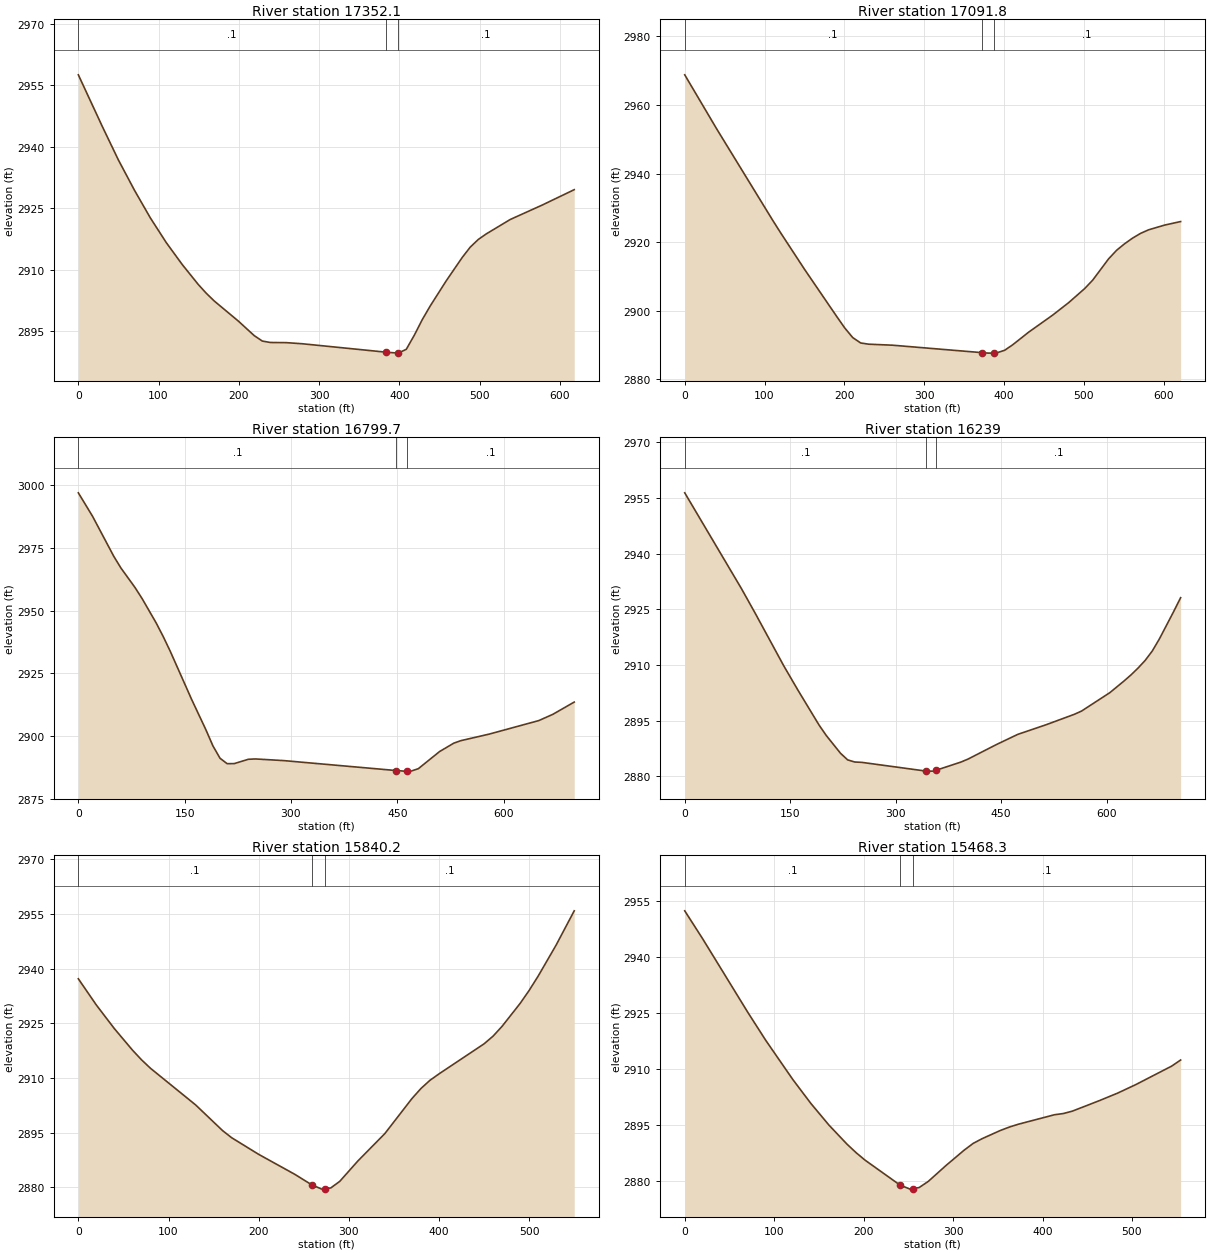
Type RM Length L Ch R = 1 ,17352.1 ,259.6,260.3,260.9
XS GIS Cut Line= 2
     2086424.643       379313.75     2086613.786       379902.14
#Sta/Elev= 30
       0 2957.57    29.9 2944.95    49.8 2936.83    69.8 2929.44    89.7 2922.64
   109.6 2916.59   129.6 2911.21   149.5 2906.36   159.5 2904.21   169.5 2902.31
   199.4 2897.43   219.3 2893.86   229.3 2892.55   239.2  2892.2   259.2 2892.16
   279.1 2891.89   383.6 2889.83   398.6  2889.6   408.7 2890.53   418.7 2893.97
   428.6 2897.77   438.6 2901.14   458.6 2907.29   478.5 2912.98   488.4 2915.48
   498.4 2917.35   508.4 2918.72   538.3 2922.24   578.2 2925.77     618 2929.52
#Mann= 3 , 0 , 0
       0      .1       0   383.6    .045       0   398.6      .1       0
Bank Sta=383.6,398.6
XS Rating Curve= 0 ,0
Exp/Cntr=0.3,0.1

Type RM Length L Ch R = 1 ,17091.8 ,287.4,292.2,296.9
XS GIS Cut Line= 2
     2086182.586      379372.472     2086357.366      379968.797
#Sta/Elev= 30
       0 2968.81    40.1 2953.01   110.2 2926.38   120.3 2922.67   150.3    2912
   190.4 2898.32   200.5 2894.96   210.5 2892.15   220.5 2890.57   230.5 2890.22
   260.6 2889.92     372 2887.76   380.9 2887.61     387 2887.66   390.9 2887.69
   400.9 2888.44   410.9 2890.03     431 2893.73     461 2898.69   481.1 2902.34
   501.1 2906.43   511.2  2908.9   531.2 2915.13   541.2 2917.62   551.2 2919.52
   561.3 2921.18   571.3 2922.56   581.3 2923.59   601.4 2924.97   621.4    2926
#Mann= 3 , 0 , 0
       0      .1       0     372    .045       0     387      .1       0
Bank Sta=372,387
XS Rating Curve= 0 ,0
Exp/Cntr=0.3,0.1

Type RM Length L Ch R = 1 ,16799.7 ,561.4,560.6,559.9
XS GIS Cut Line= 2
     2085970.748      379351.204     2086024.952      380048.714
#Sta/Elev= 30
       0 2997.05      20 2987.72      50 2971.72      60 2967.08      80 2959.25
      90 2954.83   109.9 2945.08   119.9 2939.61   129.9 2933.68   159.9 2914.56
   179.9 2902.54   189.9 2896.05   199.9 2891.12   209.9 2888.96   219.9 2888.98
   239.9 2890.71   249.9 2890.84   289.8 2890.18   448.6 2886.21   459.8 2885.98
   463.6 2885.99   469.7 2886.01   479.7 2886.96   509.7  2893.8   529.7 2897.14
   539.7 2898.14   579.7 2900.76   649.6 2906.15   669.6 2908.67   699.6 2913.54
#Mann= 3 , 0 , 0
       0      .1       0   448.6    .045       0   463.6      .1       0
Bank Sta=448.6,463.6
XS Rating Curve= 0 ,0
Exp/Cntr=0.3,0.1

Type RM Length L Ch R = 1 ,16239   ,388.7,398.8,408.9
XS GIS Cut Line= 2
     2085566.043       379381.92     2085623.357      380084.787
#Sta/Elev= 30
       0 2956.41    80.6  2930.6   100.7 2923.78     141 2909.71   161.2 2903.14
   191.4 2893.69   201.5 2890.93   221.6 2886.18   231.7 2884.41   241.8 2883.84
   251.9 2883.74   342.8  2881.4   352.6 2881.38   357.8 2881.64   392.9 2883.83
     403 2884.64   443.3 2888.55   473.5 2891.28   513.8 2893.88   554.1  2896.7
   564.2 2897.56   604.5 2902.53   624.6 2905.66   634.7 2907.33   644.8 2909.19
   654.8 2911.23   664.9 2913.77     675 2917.02   695.1 2924.32   705.2 2928.14
#Mann= 3 , 0 , 0
       0      .1       0   342.8    .045       0   357.8      .1       0
Bank Sta=342.8,357.8
XS Rating Curve= 0 ,0
Exp/Cntr=0.3,0.1

Type RM Length L Ch R = 1 ,15840.2 ,364.1,371.9,379.6
XS GIS Cut Line= 2
     2085301.071      379422.014     2085109.252      379937.362
#Sta/Elev= 30
       0 2937.25      20 2930.05      40 2923.57      60 2917.69      70 2915.04
      80  2912.7     130 2902.66     160 2895.59     170 2893.65     200 2889.08
     240 2883.61   258.7 2880.74     270 2879.54   273.7 2879.66   279.9 2879.86
   289.9 2881.67   309.9 2887.24   339.9 2894.78   369.9 2904.37   379.9 2907.14
   389.9 2909.39   399.9 2911.15   449.9  2919.4   459.9 2921.51   469.9 2924.21
   489.9 2930.49   499.9 2934.05   509.9 2937.98   529.9 2946.53   549.9  2955.9
#Mann= 3 , 0 , 0
       0      .1       0   258.7    .045       0   273.7      .1       0
Bank Sta=258.7,273.7
XS Rating Curve= 0 ,0
Exp/Cntr=0.3,0.1

Type RM Length L Ch R = 1 ,15468.3 ,363.2,349.4,335.1
XS GIS Cut Line= 2
     2085101.151       379237.83     2084741.296      379659.612
#Sta/Elev= 30
       0 2952.37    20.2 2944.83    70.6 2925.19    90.7 2917.69     121  2907.2
   141.1 2900.83   161.3 2895.05   181.4 2889.97   191.5 2887.71   201.6 2885.69
   240.7 2879.02     252 2877.94   255.7 2878.09   262.1 2878.37   272.2 2879.99
   292.3  2884.3   312.5 2888.38   322.6 2890.19   332.7 2891.46   352.8 2893.62
   362.9 2894.54     373  2895.3   413.3 2897.83   423.4 2898.16   433.5 2898.81
   463.7 2901.62   483.9 2903.61     504 2905.86   544.4 2910.84   554.4 2912.47
#Mann= 3 , 0 , 0
       0      .1       0   240.7    .045       0   255.7      .1       0
Bank Sta=240.7,255.7
XS Rating Curve= 0 ,0
Exp/Cntr=0.3,0.1