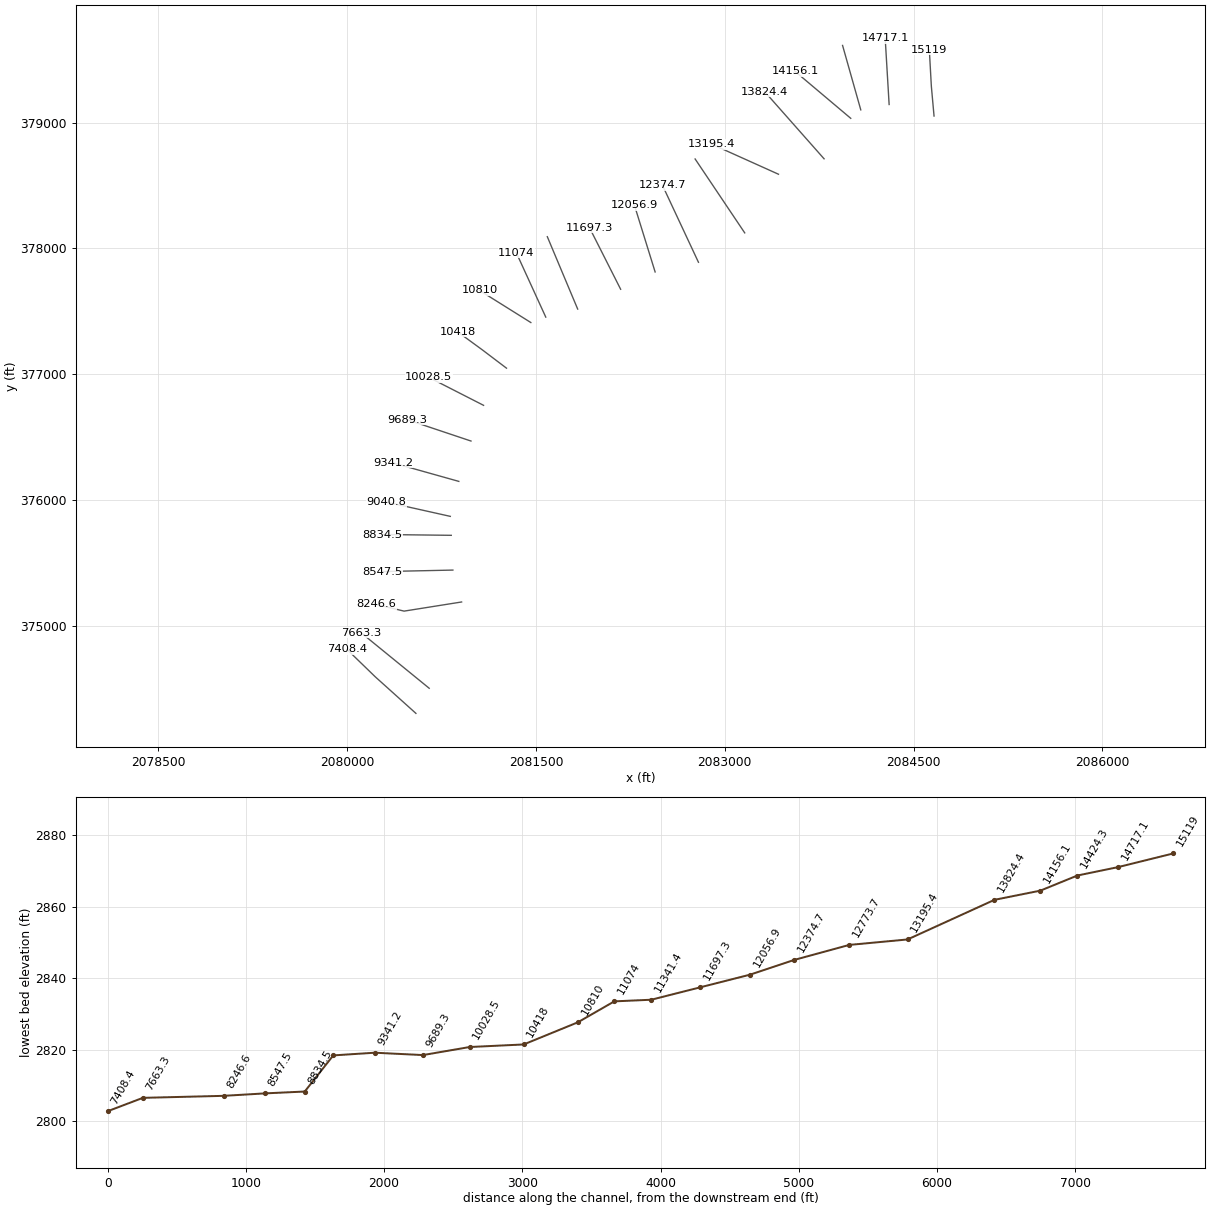
HEC-RAS study SFkBigClCk.prj: SFkBigClCk

--- SFkBigClCk.g01 (geometry) --- (continued)

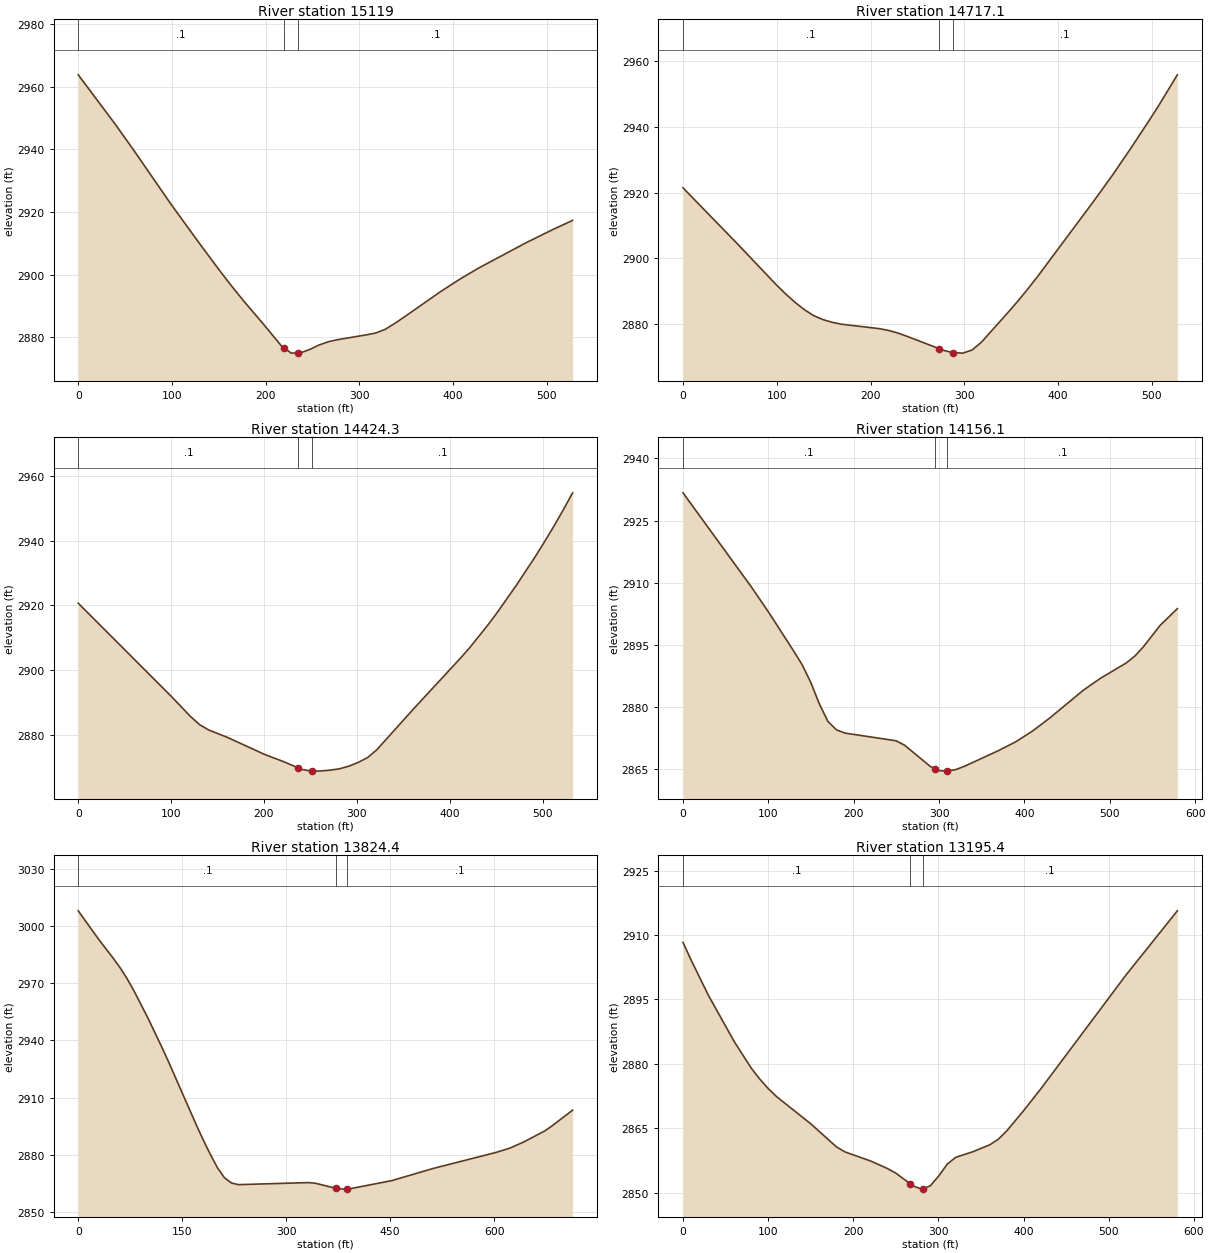
Type RM Length L Ch R = 1 ,15119   ,402.4,401.9,401.8
XS GIS Cut Line= 3
     2084663.033      379052.421     2084641.687      379288.776
     2084625.586      379578.762
#Sta/Elev= 30
       0 2963.83    39.6    2948    59.3 2939.72    98.9 2922.55   128.6 2910.29
   148.3 2902.36   158.2 2898.47   168.1 2894.71     178  2891.1   197.8 2884.15
   217.5 2877.01   219.7 2876.56   227.4 2874.92   234.7 2874.98   237.3    2875
   247.3 2876.11   257.4 2877.56   267.4 2878.59   277.4 2879.24   307.4 2880.75
   317.4 2881.34   327.4 2882.47   337.5 2884.32   347.5 2886.35   387.5 2894.71
   407.6 2898.58   427.6 2902.12   477.7 2910.12   507.7 2914.55   527.8 2917.32
#Mann= 3 , 0 , 0
       0      .1       0   219.7    .045       0   234.7      .1       0
Bank Sta=219.7,234.7
XS Rating Curve= 0 ,0
Exp/Cntr=0.3,0.1

Type RM Length L Ch R = 1 ,14717.1 ,287.8,292.8,297.7
XS GIS Cut Line= 2
     2084306.166      379144.059     2084274.873      379670.206
#Sta/Elev= 30
       0 2921.45    59.7 2903.89    99.4 2891.92   109.4 2889.14   119.3  2886.6
   129.3 2884.34   139.2 2882.52   149.2 2881.29   159.1 2880.46   169.1 2879.88
   208.8 2878.55   218.8 2878.02   228.7 2877.23   238.7 2876.22   272.7 2872.48
   278.5 2871.87   287.7 2871.23   298.4 2871.07   308.3 2872.03   318.2  2874.4
   348.1 2883.96     358 2887.25     368 2890.74   377.9 2894.34   437.6 2917.26
   457.5 2925.13   477.4 2933.46   497.2 2942.04   507.2  2946.5   527.1 2955.89
#Mann= 3 , 0 , 0
       0      .1       0   272.7    .045       0   287.7      .1       0
Bank Sta=272.7,287.7
XS Rating Curve= 0 ,0
Exp/Cntr=0.3,0.1

Type RM Length L Ch R = 1 ,14424.3 ,254.7,268.2,281.9
XS GIS Cut Line= 2
      2084080.91      379101.336     2083936.235      379613.656
#Sta/Elev= 30
       0 2920.66   100.4  2891.8   120.5 2885.74   130.6 2883.13   140.6 2881.44
   160.7 2879.16   200.9 2873.87     221 2871.68   237.1 2869.71   241.1 2869.25
   251.1 2868.73   252.1 2868.74   261.2 2868.78   271.2 2869.03   281.2 2869.44
   291.3 2870.25   301.3 2871.39   311.4 2872.88   321.4  2875.3   361.6 2888.14
   411.8 2903.73   421.9 2907.03     442 2914.24     452 2918.11   472.1 2926.35
   492.2 2935.09   502.2  2939.7   512.3 2944.52   522.3 2949.52   532.4 2954.81
#Mann= 3 , 0 , 0
       0      .1       0   237.1    .045       0   252.1      .1       0
Bank Sta=237.1,252.1
XS Rating Curve= 0 ,0
Exp/Cntr=0.3,0.1

Type RM Length L Ch R = 1 ,14156.1 ,335.1,331.7,328.2
XS GIS Cut Line= 2
     2084001.107      379034.252     2083558.363      379407.684
#Sta/Elev= 30
       0  2931.7    79.9 2909.03    99.9 2903.01   129.8 2893.46   139.8 2890.13
   149.8 2885.87   159.8 2880.72   169.8 2876.49   179.8 2874.46   189.7 2873.68
   249.7 2871.82   259.6 2870.76   289.6 2865.65   294.8 2865.11   299.6 2864.62
   309.6 2864.49   309.8  2864.5   319.6 2864.86   329.6 2865.64   369.5 2869.43
   389.5 2871.53   409.4 2874.15   429.4 2877.27   469.4 2884.08   489.3 2886.93
   519.3 2890.61   529.3 2892.26   539.3 2894.48   559.2 2899.73   579.2 2903.73
#Mann= 3 , 0 , 0
       0      .1       0   294.8    .045       0   309.8      .1       0
Bank Sta=294.8,309.8
XS Rating Curve= 0 ,0
Exp/Cntr=0.3,0.1

Type RM Length L Ch R = 1 ,13824.4 ,618.8,629,639.2
XS GIS Cut Line= 2
     2083789.291      378712.262     2083317.024      379246.622
#Sta/Elev= 30
       0 3007.96    30.1 2992.68    50.2 2983.21    60.3 2978.14    70.3 2972.45
    80.4 2965.94   100.4 2951.79   120.5 2936.48   130.6 2928.48   170.8  2895.2
   180.8 2887.38   190.8 2879.97   200.9 2873.11   210.9 2867.89     221 2865.15
     231 2864.28   331.5 2865.34   341.5 2865.06   372.2 2862.31   381.7 2861.92
   387.2 2862.02   391.7  2862.1     452 2866.35   512.3 2872.79   602.7 2881.17
   622.8 2883.45   642.8 2886.68     673 2892.46     683 2894.96   713.2 2903.36
#Mann= 3 , 0 , 0
       0      .1       0   372.2    .045       0   387.2      .1       0
Bank Sta=372.2,387.2
XS Rating Curve= 0 ,0
Exp/Cntr=0.3,0.1

Type RM Length L Ch R = 1 ,13195.4 ,434.2,421.7,409.1
XS GIS Cut Line= 2
     2083427.063       378589.58     2082897.547      378828.002
#Sta/Elev= 30
       0  2908.3      10 2903.98      30 2895.91    60.1 2885.22    80.1 2879.03
    90.1 2876.48   100.1 2874.25   110.1 2872.34   150.2 2866.02   180.2 2860.67
   190.2  2859.5   220.3 2857.38   240.3 2855.61   250.3 2854.51   267.1 2852.03
   270.3 2851.56   280.4 2850.82   282.1 2850.96   290.4 2851.57   300.4 2853.88
   310.4 2856.63   320.4 2858.24   340.4 2859.52   360.4 2861.15   370.5 2862.45
   380.5 2864.43   400.5 2869.18   420.5 2874.22   520.6 2900.74   580.7 2915.64
#Mann= 3 , 0 , 0
       0      .1       0   267.1    .045       0   282.1      .1       0
Bank Sta=267.1,282.1
XS Rating Curve= 0 ,0
Exp/Cntr=0.3,0.1

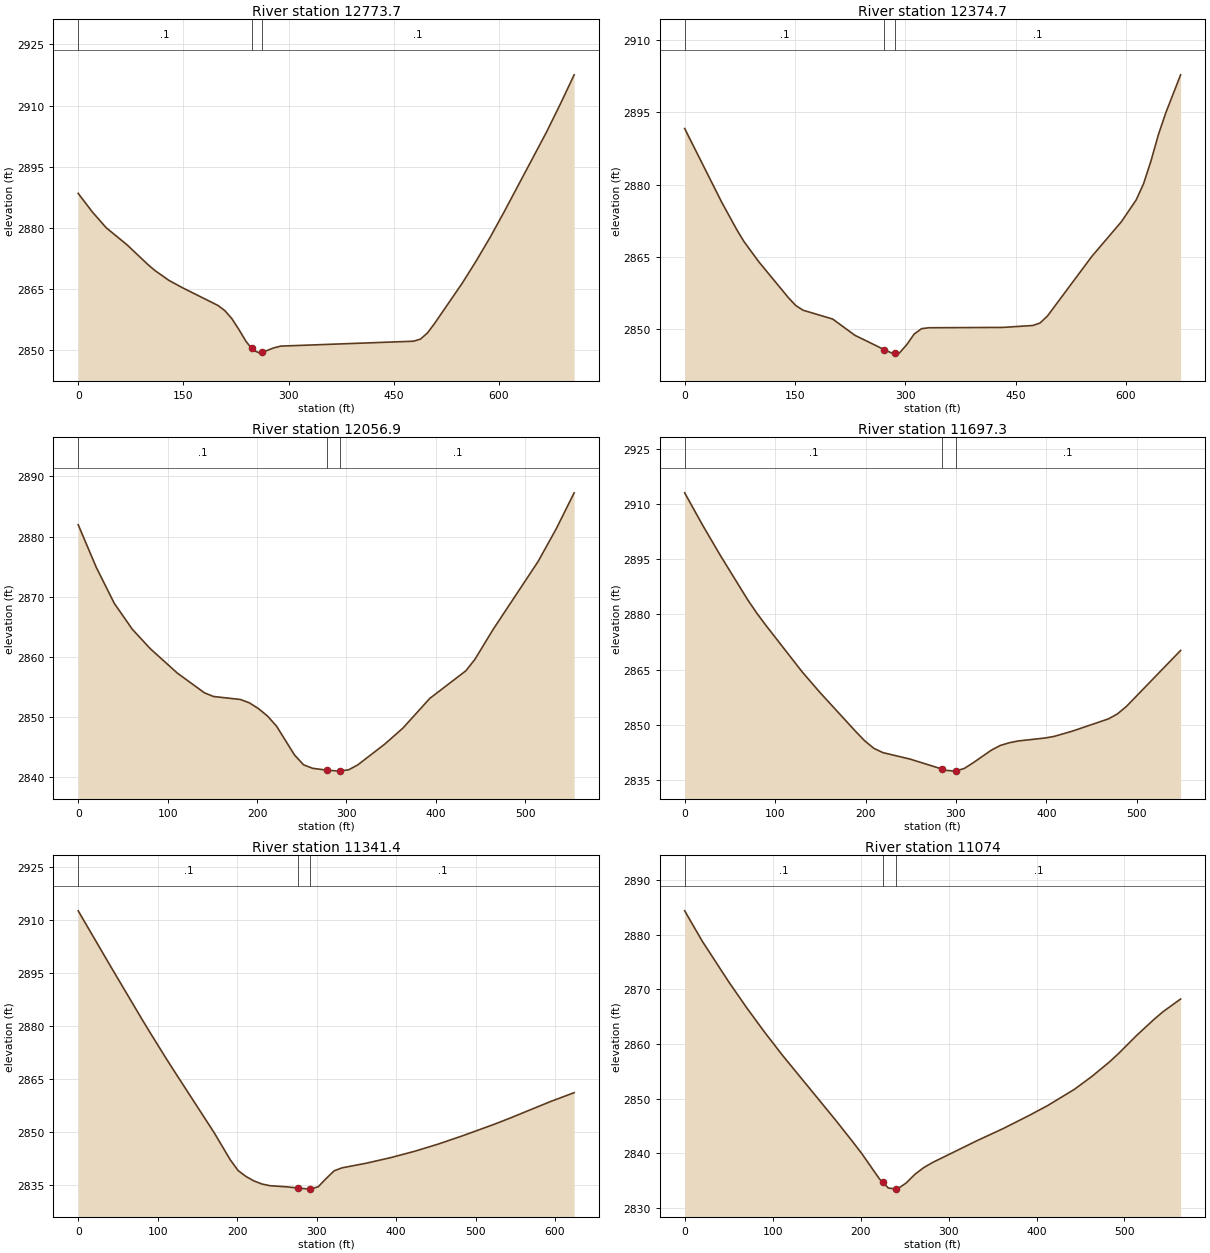
Type RM Length L Ch R = 1 ,12773.7 ,402.6,399,395.4
XS GIS Cut Line= 2
     2083158.665      378123.362     2082764.573      378710.984
#Sta/Elev= 30
       0 2888.46    19.9 2883.96    39.9 2880.04    69.8 2875.83    99.6 2870.98
   109.6 2869.53   129.6 2867.11   149.5 2865.26   199.3 2860.99   209.3 2859.69
   219.2 2857.74   229.2  2855.1   239.2 2852.22   247.4 2850.43   249.1 2850.05
   259.1 2849.29   262.4 2849.46     279 2850.58     289 2851.01   478.3 2852.21
   488.3 2852.73   498.3 2854.25   508.2 2856.52   548.1  2866.5     568 2871.97
     588 2877.79   607.9 2884.02   667.7 2903.37   687.6  2910.3   707.5 2917.53
#Mann= 3 , 0 , 0
       0      .1       0   247.4    .045       0   262.4      .1       0
Bank Sta=247.4,262.4
XS Rating Curve= 0 ,0
Exp/Cntr=0.3,0.1

Type RM Length L Ch R = 1 ,12374.7 ,321,317.8,314.7
XS GIS Cut Line= 2
     2082791.057      377889.604      2082505.58      378500.615
#Sta/Elev= 30
       0 2891.62    50.3 2876.37    70.5 2870.76    80.5 2868.23   100.7 2864.03
   140.9  2856.6     151 2854.95     161 2853.97   201.3 2852.14   231.5 2848.77
   271.2 2845.82   281.8 2845.08   286.2 2845.08   291.9 2845.09     302 2846.83
     312 2849.02   322.1 2850.15   332.2 2850.34   432.8 2850.41   473.1  2850.8
   483.2 2851.32   493.2 2852.75   553.6 2865.11   593.9 2872.32     614 2876.83
   624.1 2880.22   634.2 2884.96   644.2 2890.36   654.3  2894.9   674.4 2902.75
#Mann= 3 , 0 , 0
       0      .1       0   271.2    .045       0   286.2      .1       0
Bank Sta=271.2,286.2
XS Rating Curve= 0 ,0
Exp/Cntr=0.3,0.1

Type RM Length L Ch R = 1 ,12056.9 ,355.5,359.6,363.6
XS GIS Cut Line= 2
      2082446.79      377812.571     2082282.535      378342.403
#Sta/Elev= 30
       0 2881.97    20.2 2874.88    40.3  2868.9    60.5 2864.58    80.7 2861.33
   110.9 2857.28   141.2    2854   151.3 2853.39   181.5 2852.89   191.6 2852.32
   201.7 2851.36   211.8 2850.13   221.9 2848.44     242 2843.64   252.1 2842.02
   262.2 2841.44   278.2 2841.13   292.5 2840.97   293.2 2840.99   302.6  2841.2
   312.6    2842   342.9 2845.47   363.1 2848.12   393.3 2853.08   433.7 2857.68
   443.8 2859.59   463.9 2864.51   514.4 2875.86   534.5 2881.25   554.7 2887.28
#Mann= 3 , 0 , 0
       0      .1       0   278.2    .045       0   293.2      .1       0
Bank Sta=278.2,293.2
XS Rating Curve= 0 ,0
Exp/Cntr=0.3,0.1

Type RM Length L Ch R = 1 ,11697.3 ,357.5,355.9,354.3
XS GIS Cut Line= 2
     2082172.736      377675.034     2081925.296      378164.501
#Sta/Elev= 30
       0 2913.06    19.9 2904.25    39.9 2895.87    69.8 2883.96    79.8 2880.35
    89.8 2877.06   129.6 2864.51   149.6 2858.81   189.5 2848.11   199.4  2845.6
   209.4  2843.6   219.4 2842.45   249.3  2840.7   284.8 2837.98   289.2 2837.64
   299.2 2837.43   299.8 2837.48   309.1 2838.14   319.1  2839.7     339  2843.1
     349  2844.4     359 2845.14     369 2845.63   398.9 2846.44   408.8 2846.88
   428.8  2848.3   468.7 2851.63   478.6 2852.98   488.6 2855.02   548.5 2870.23
#Mann= 3 , 0 , 0
       0      .1       0   284.8    .045       0   299.8      .1       0
Bank Sta=284.8,299.8
XS Rating Curve= 0 ,0
Exp/Cntr=0.3,0.1

Type RM Length L Ch R = 1 ,11341.4 ,266.7,267.5,268.2
XS GIS Cut Line= 2
     2081831.385      377517.412     2081590.045       378092.96
#Sta/Elev= 30
       0 2912.61    40.3  2897.1    80.5 2881.87    90.6 2878.14   110.7 2870.87
   120.8 2867.32   171.1 2849.89   191.3 2842.25   201.3 2839.18   211.4 2837.48
   221.4 2836.23   231.5 2835.37   241.6  2834.9   261.7  2834.6   277.2 2834.23
   291.9 2833.94   292.2 2833.95     302  2834.6     312 2836.94   322.1 2839.12
   332.2 2839.97   362.4 2841.26   392.6 2842.81   422.8  2844.6     453 2846.67
   483.2 2848.98   523.4 2852.26   543.6 2854.03   593.9 2858.66   624.1 2861.21
#Mann= 3 , 0 , 0
       0      .1       0   277.2    .045       0   292.2      .1       0
Bank Sta=277.2,292.2
XS Rating Curve= 0 ,0
Exp/Cntr=0.3,0.1

Type RM Length L Ch R = 1 ,11074   ,250.7,263.9,277.2
XS GIS Cut Line= 2
     2081577.776      377453.503     2081343.391      377966.307
#Sta/Elev= 30
       0 2884.39    20.1 2878.81    50.3 2871.35    70.5 2866.66    90.6 2862.25
   110.8 2858.04   171.2 2846.18   191.3 2842.09   201.4 2839.97   221.5 2835.33
   225.2 2834.73   231.6 2833.68   240.2 2833.51   241.6 2833.48   251.7 2834.59
   261.8  2836.2   271.8 2837.42   281.9 2838.36   332.3 2842.34   362.5 2844.59
   392.7 2847.05   412.8 2848.78     443 2851.73   463.2 2854.13   483.3  2856.8
   493.4 2858.31   513.5 2861.55   533.6 2864.54   543.7 2865.92   563.8 2868.26
#Mann= 3 , 0 , 0
       0      .1       0   225.2    .045       0   240.2      .1       0
Bank Sta=225.2,240.2
XS Rating Curve= 0 ,0
Exp/Cntr=0.3,0.1

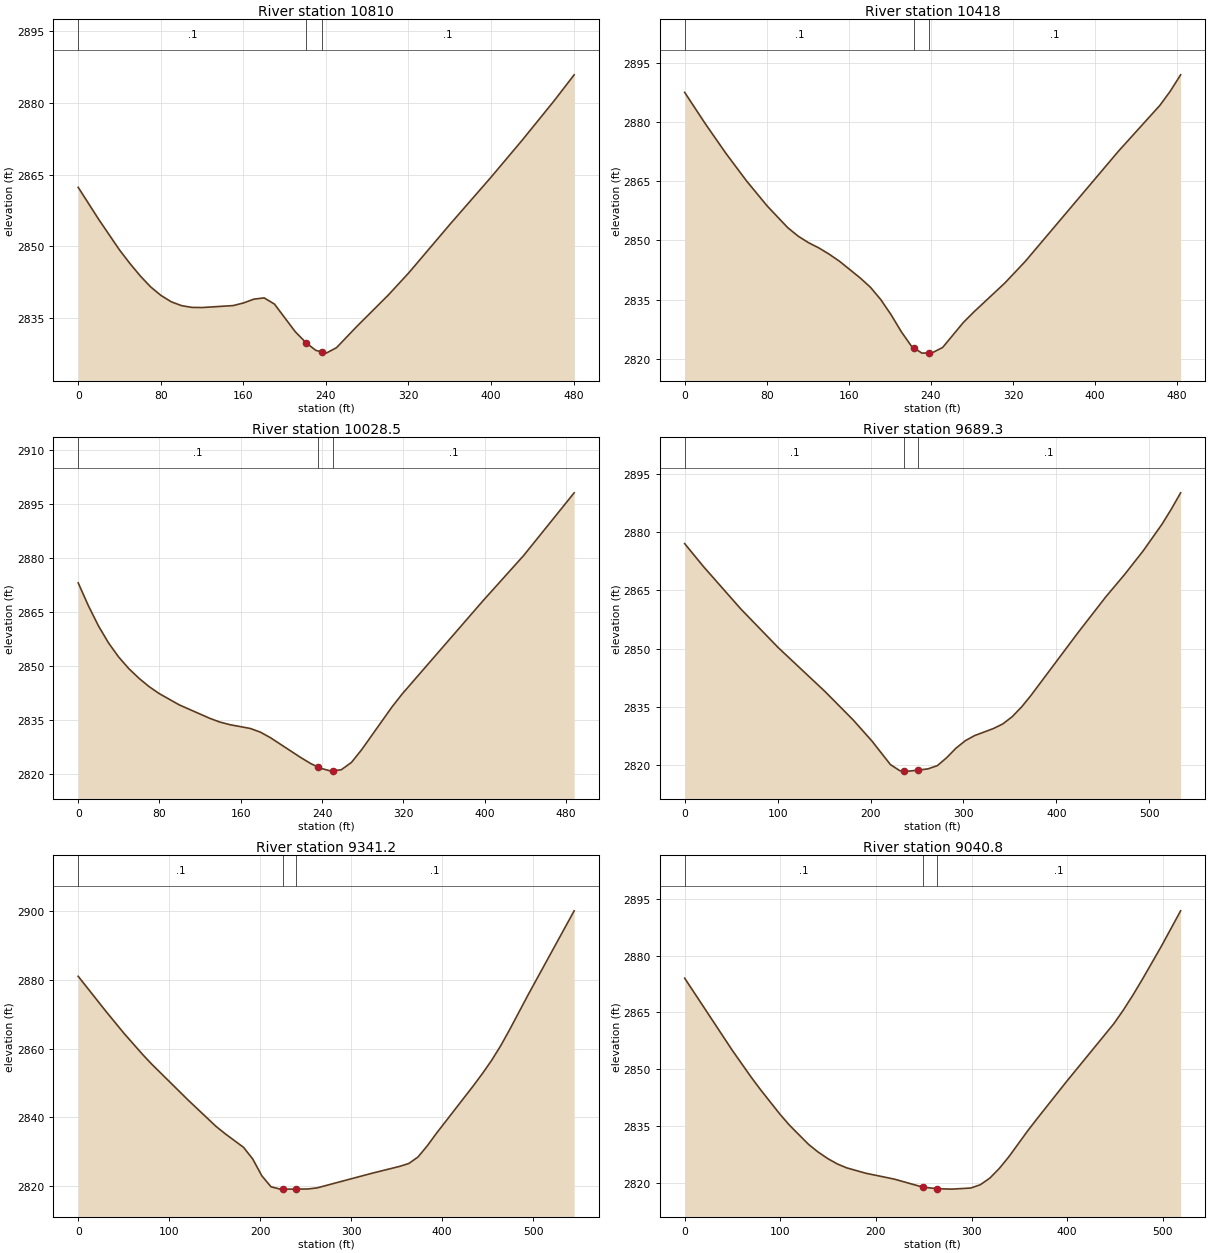
Type RM Length L Ch R = 1 ,10810   ,394,392,390.2
XS GIS Cut Line= 2
     2081459.252      377410.346     2081051.932      377665.453
#Sta/Elev= 30
       0 2862.33      20 2855.58      40 2849.23    50.1 2846.39    60.1 2843.79
    70.1  2841.5    80.1 2839.71    90.1 2838.37   100.1 2837.56   110.1 2837.19
   120.2 2837.16   150.2 2837.57   160.2 2838.12   170.2 2838.91   180.2 2839.18
   190.2 2837.88   210.3  2832.1   221.2  2829.7   230.3 2828.19   236.2 2827.85
   240.3 2827.61   250.3 2828.75   270.3 2833.27   300.4 2839.75   320.4 2844.44
   360.5 2854.65   400.5 2864.57   430.6  2872.3   460.6  2880.3   480.6  2885.9
#Mann= 3 , 0 , 0
       0      .1       0   221.2    .045       0   236.2      .1       0
Bank Sta=221.2,236.2
XS Rating Curve= 0 ,0
Exp/Cntr=0.3,0.1

Type RM Length L Ch R = 1 ,10418   ,385.5,389.5,393.3
XS GIS Cut Line= 3
     2081265.637       377047.63     2081073.359      377193.359
     2080877.974      377336.248
#Sta/Elev= 30
       0 2887.58    20.1 2879.63    40.2 2872.11    60.3 2865.11    80.4 2858.76
   100.5 2853.23   110.6  2851.1   120.6 2849.45   130.7 2848.12   140.7 2846.54
   150.8 2844.74   170.9 2840.52     181 2838.13     191 2835.03     201 2831.22
   211.1 2826.85   221.2  2823.1   223.4 2822.73   231.2 2821.41   238.4 2821.48
   241.3 2821.51   251.4 2822.85   271.5 2829.17   281.6 2831.81   311.9 2839.17
     332 2844.72   422.8 2872.68   463.2 2884.32   473.2 2887.88   483.3 2892.04
#Mann= 3 , 0 , 0
       0      .1       0   223.4    .045       0   238.4      .1       0
Bank Sta=223.4,238.4
XS Rating Curve= 0 ,0
Exp/Cntr=0.3,0.1

Type RM Length L Ch R = 1 ,10028.5 ,335.9,339.2,342.6
XS GIS Cut Line= 2
     2081083.509       376752.13     2080648.788      376974.206
#Sta/Elev= 30
       0 2873.12      10 2866.77    19.9 2861.16    29.9 2856.38    39.8 2852.49
    49.8 2849.25    59.8 2846.56    69.7 2844.25    79.7  2842.3    99.6 2839.13
   129.5 2835.41   139.5 2834.36   149.4 2833.63   169.4 2832.58   179.3 2831.56
   189.3    2830   219.2 2824.46   229.1 2822.77   235.8  2821.9   239.1 2821.46
   249.1  2820.7   250.8 2820.76     259 2821.09     269 2823.13     279 2826.66
   308.8 2838.54   318.8 2842.15   398.5 2868.15   438.4 2880.71   488.2  2898.2
#Mann= 3 , 0 , 0
       0      .1       0   235.8    .045       0   250.8      .1       0
Bank Sta=235.8,250.8
XS Rating Curve= 0 ,0
Exp/Cntr=0.3,0.1

Type RM Length L Ch R = 1 ,9689.3  ,347,348.1,360.8
XS GIS Cut Line= 2
     2080983.623      376468.133     2080477.566      376637.653
#Sta/Elev= 30
       0    2877    20.1 2871.13    60.4 2860.19   100.7 2850.23     151 2838.94
   181.3 2831.62   201.4 2826.22   221.5 2820.11   231.6 2818.54   235.9 2818.49
   241.7 2818.44   250.9  2818.7   261.8 2819.02   271.9 2819.85     282 2821.91
     292 2824.36   302.1 2826.29   312.2 2827.61   332.3 2829.41   342.4  2830.6
   352.4 2832.44   362.5 2834.94   372.6 2837.91   422.9 2853.97   453.1 2863.28
   473.3 2869.02   493.4 2875.14   513.6 2881.98   523.6 2885.85   533.7 2890.08
#Mann= 3 , 0 , 0
       0      .1       0   235.9    .045       0   250.9      .1       0
Bank Sta=235.9,250.9
XS Rating Curve= 0 ,0
Exp/Cntr=0.3,0.1

Type RM Length L Ch R = 1 ,9341.2  ,299.2,300.4,301.6
XS GIS Cut Line= 2
     2080886.894      376147.322     2080362.217      376294.754
#Sta/Elev= 30
       0 2881.03    30.3  2870.9    50.5 2864.38    70.6 2858.34    80.7  2855.5
   121.1 2844.94   151.4 2837.37   161.5 2835.22   181.7 2831.26   191.8 2827.86
   201.8 2822.97   211.9 2819.78     222  2819.1   224.7  2819.1   239.7 2819.11
   252.3 2819.14   262.4 2819.45     323 2823.73   353.2 2825.72   363.3 2826.56
   373.4 2828.45   383.5 2831.67   393.6 2835.32     434  2849.1   444.1  2852.7
   454.2 2856.53   464.3 2860.83   474.4 2865.65   494.5 2875.69     545 2900.09
#Mann= 3 , 0 , 0
       0      .1       0   224.7    .045       0   239.7      .1       0
Bank Sta=224.7,239.7
XS Rating Curve= 0 ,0
Exp/Cntr=0.3,0.1

Type RM Length L Ch R = 1 ,9040.8  ,201.7,206.4,211.1
XS GIS Cut Line= 2
     2080819.198      375869.183     2080313.079      375982.367
#Sta/Elev= 30
       0 2874.04    49.9 2854.96    69.8 2847.82    79.8 2844.45    99.7 2838.11
   109.7  2835.2   129.6 2830.15   139.6 2828.13   149.6 2826.42   159.6    2825
   169.6 2823.95   189.5 2822.54   219.4 2820.98   248.8 2818.89   263.8 2818.46
   279.3 2818.35   299.2 2818.64   309.2 2819.52   319.2 2821.28   329.1 2823.84
   339.1 2826.93     359 2833.85     369  2837.1   398.9 2846.63   448.8 2862.04
   458.8 2865.66   468.8 2869.61   478.7 2873.79   498.7 2882.58   518.6 2891.83
#Mann= 3 , 0 , 0
       0      .1       0   248.8    .045       0   263.8      .1       0
Bank Sta=248.8,263.8
XS Rating Curve= 0 ,0
Exp/Cntr=0.3,0.1

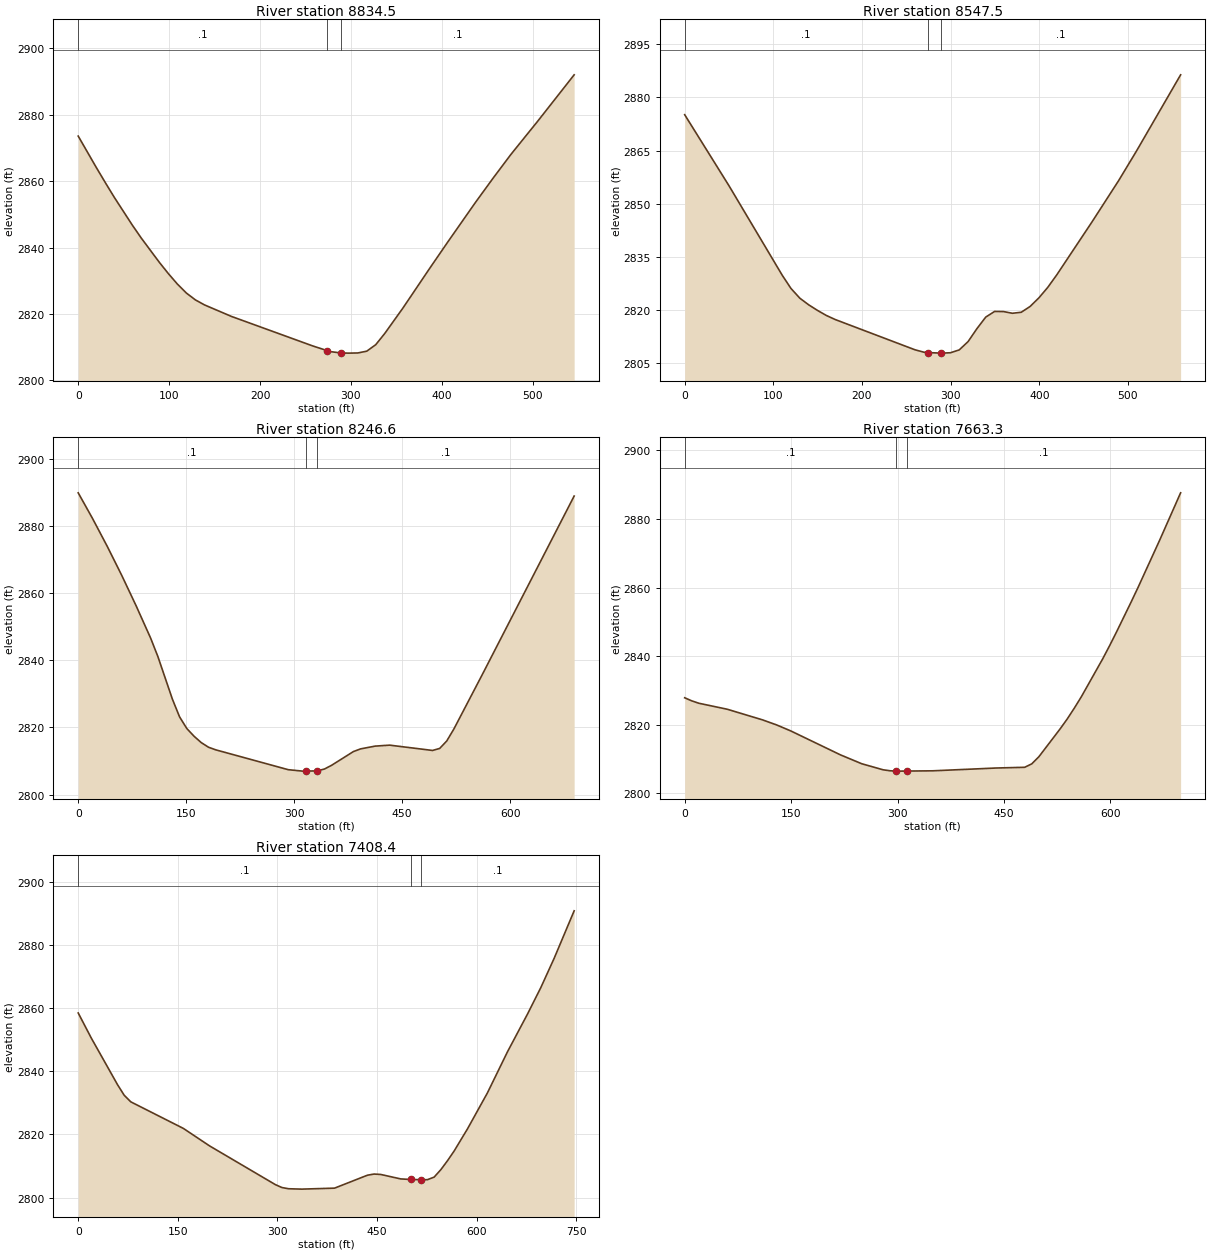
Type RM Length L Ch R = 1 ,8834.5  ,286.2,286.9,287.7
XS GIS Cut Line= 2
     2080826.938      375718.467      2080281.44      375724.923
#Sta/Elev= 30
       0 2873.54    19.8 2864.14    29.8 2859.55    39.7 2855.11    59.5 2846.76
    69.4 2842.84    89.3 2835.53    99.2 2832.15   109.1 2829.01     119 2826.31
   128.9 2824.25   138.9 2822.74   168.6 2819.27   257.9  2810.4     274 2808.97
   277.7 2808.67     289 2808.28   297.6 2808.23   307.5 2808.28   317.4 2808.82
   327.3 2810.78   337.2 2814.15   357.1 2821.77   386.8 2833.82   406.7 2841.75
   436.4 2853.37   456.3 2860.87   476.1 2868.08   505.9 2878.19   545.5 2891.98
#Mann= 3 , 0 , 0
       0      .1       0     274    .045       0     289      .1       0
Bank Sta=274,289
XS Rating Curve= 0 ,0
Exp/Cntr=0.3,0.1

Type RM Length L Ch R = 1 ,8547.5  ,297.8,300.9,304
XS GIS Cut Line= 2
     2080839.877      375442.039     2080280.595      375430.129
#Sta/Elev= 30
       0 2875.13      50 2855.03   109.9 2829.79   119.9 2825.99   129.9 2823.24
   139.8 2821.38   149.8 2819.79   159.8 2818.36   169.8 2817.21   259.7 2808.66
   269.7 2807.98     274 2807.87     289 2807.71   299.7 2807.81   309.7 2808.62
   319.7 2810.98   329.6 2814.61   339.6  2817.9   349.6  2819.5   359.6 2819.46
   369.6 2818.98   379.6 2819.26   389.6  2820.9   399.6 2823.35   409.6 2826.32
   419.6  2829.8   459.5 2844.83   489.5 2856.49   509.5  2864.8   559.4  2886.4
#Mann= 3 , 0 , 0
       0      .1       0     274    .045       0     289      .1       0
Bank Sta=274,289
XS Rating Curve= 0 ,0
Exp/Cntr=0.3,0.1

Type RM Length L Ch R = 1 ,8246.6  ,601.5,583.4,568.8
XS GIS Cut Line= 3
     2080909.021      375188.432      2080452.02      375115.726
     2080232.091      375168.601
#Sta/Elev= 30
       0 2889.81    20.1  2882.1    40.2 2873.94    60.4 2865.28    80.5 2856.18
   100.6 2846.59   110.7 2841.09   130.8 2828.45   140.8 2823.16   150.9 2819.68
     161 2817.38     171 2815.49   181.1 2814.12   191.1 2813.35   291.7 2807.45
   311.8 2807.02   316.8 2807.02   331.8  2807.1     342 2807.64   352.1 2808.77
   382.3 2812.84   392.3 2813.64   412.4 2814.46   432.6 2814.75   492.2 2813.17
   502.1 2813.77   511.9 2815.98   521.8 2819.54   561.1 2835.66   688.9 2888.85
#Mann= 3 , 0 , 0
       0      .1       0   316.8    .045       0   331.8      .1       0
Bank Sta=316.8,331.8
XS Rating Curve= 0 ,0
Exp/Cntr=0.3,0.1

Type RM Length L Ch R = 1 ,7663.3  ,258.1,254.8,248
XS GIS Cut Line= 2
     2080651.489      374502.294     2080109.852      374944.001
#Sta/Elev= 30
       0 2827.86      10 2826.96      20 2826.26    59.9 2824.52   109.8 2821.41
   129.8 2819.92   149.8 2818.16   219.7 2811.19   249.6 2808.61   279.6 2806.85
   289.6 2806.56     298 2806.47   299.5 2806.46     313 2806.48   349.5 2806.55
   439.3 2807.37   479.2 2807.58   489.2 2808.59   499.2 2810.67   529.2 2818.81
   539.2  2821.7   549.1 2824.84   559.1 2828.19   589.1 2839.22   599.1 2843.16
     609 2847.24     629 2855.73     639 2860.09     669 2873.66   698.9 2887.65
#Mann= 3 , 0 , 0
       0      .1       0     298    .045       0     313      .1       0
Bank Sta=298,313
XS Rating Curve= 0 ,0
Exp/Cntr=0.3,0.1

Type RM Length L Ch R = 1 ,7408.4  ,652.6,647.8,643.2
XS GIS Cut Line= 3
     2080546.032      374302.652     2080222.243      374594.015
     2079998.715      374810.925
#Sta/Elev= 30
       0 2858.45    19.8 2850.47    59.4  2835.7    69.3 2832.41    79.2 2830.33
   158.4 2821.92     198 2816.37     297 2804.13   306.9 2803.21   316.8 2802.83
   336.6 2802.71   386.1 2803.02   435.6 2807.11   445.6 2807.48   455.7 2807.35
   485.8 2805.94     501 2805.76     516  2805.7     526  2805.7   536.1 2806.51
   546.1 2808.84   556.2 2811.69   566.2 2814.76   586.3 2821.76   616.4 2833.17
   646.6 2846.17   676.7 2858.09   696.8 2866.48   716.9 2875.75     747 2890.77
#Mann= 3 , 0 , 0
       0      .1       0     501    .045       0     516      .1       0
Bank Sta=501,516
XS Rating Curve= 0 ,0
Exp/Cntr=0.3,0.1