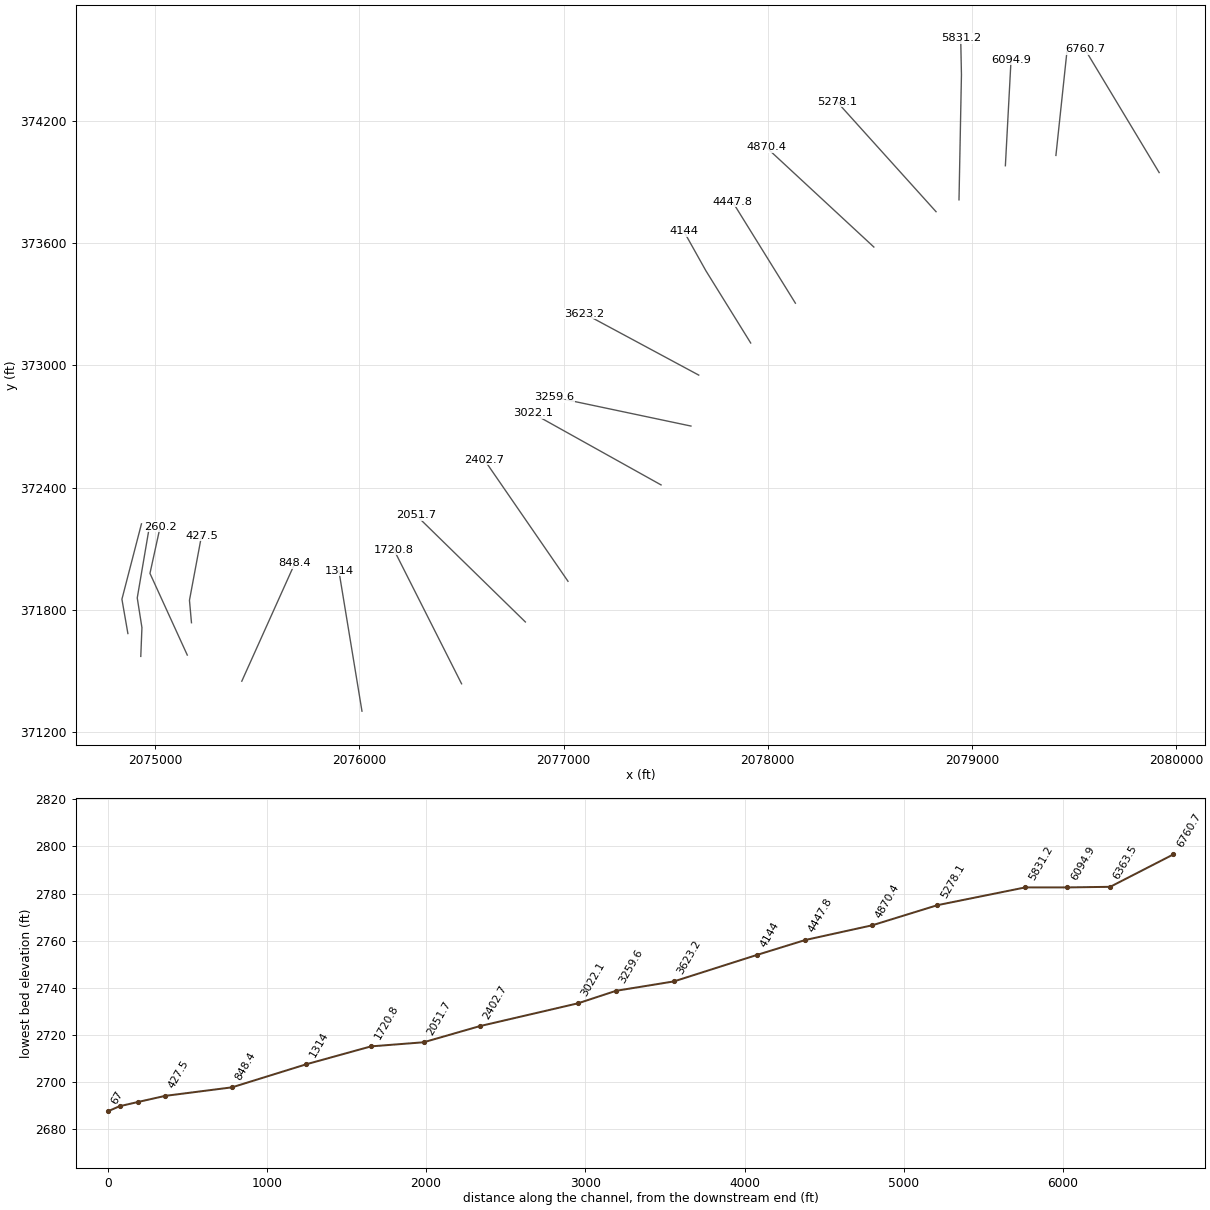
HEC-RAS study SFkBigClCk.prj: SFkBigClCk

--- SFkBigClCk.g01 (geometry) --- (continued)

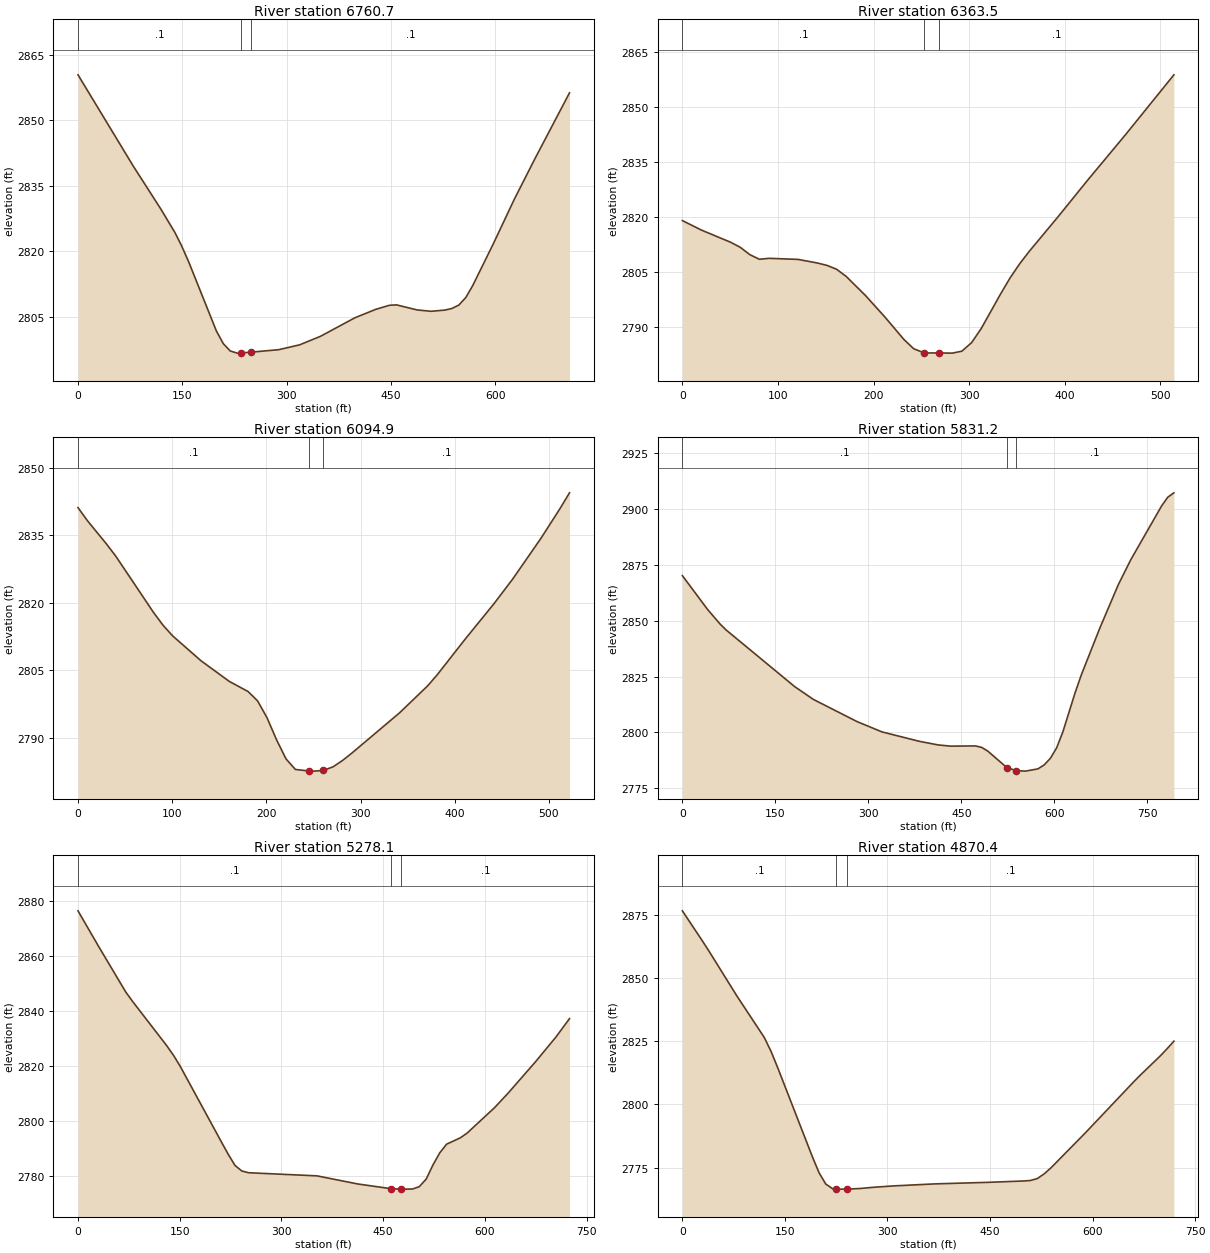
Type RM Length L Ch R = 1 ,6760.7  ,412.8,397.1,381.2
XS GIS Cut Line= 2
     2079917.457      373945.553     2079553.375      374551.477
#Sta/Elev= 30
       0 2860.39    79.6 2839.46   119.5 2829.56   139.4 2824.28   149.3 2821.13
   159.3 2817.52   199.1  2801.7   209.1  2798.8     219 2797.14     229 2796.65
   233.9 2796.68   248.9 2796.87   288.7 2797.44   318.6 2798.54   348.5 2800.48
   398.2 2804.74   428.1 2806.67     448 2807.61     458  2807.7   487.9 2806.54
   507.8 2806.23   527.7 2806.51   537.6 2806.87   547.6 2807.64   557.6 2809.35
   567.5 2812.06   597.4 2821.72   627.2 2831.79   657.1 2841.16   706.9 2856.27
#Mann= 3 , 0 , 0
       0      .1       0   233.9    .045       0   248.9      .1       0
Bank Sta=233.9,248.9
XS Rating Curve= 0 ,0
Exp/Cntr=0.3,0.1

Type RM Length L Ch R = 1 ,6363.5  ,267.4,268.6,269.8
XS GIS Cut Line= 2
     2079411.766      374029.702     2079465.895      374540.954
#Sta/Elev= 30
       0 2819.04    20.2 2816.42    50.4 2813.14    60.5 2811.76    70.6 2809.74
    80.6 2808.48    90.7 2808.74     121 2808.45   141.1 2807.47   151.2 2806.82
   161.3 2805.76   171.4 2803.79   191.5  2798.6   211.7 2792.76   231.8 2786.57
   241.9 2784.08     253 2782.92     268 2782.92   282.3 2782.87   292.3  2783.4
   302.4  2785.7   312.5 2789.55   332.7 2798.96   342.7 2803.37   352.8 2807.26
   362.9 2810.67   393.1 2820.14   423.4 2829.91   463.7 2842.55   514.1 2858.82
#Mann= 3 , 0 , 0
       0      .1       0     253    .045       0     268      .1       0
Bank Sta=253,268
XS Rating Curve= 0 ,0
Exp/Cntr=0.3,0.1

Type RM Length L Ch R = 1 ,6094.9  ,262.3,263.7,265.2
XS GIS Cut Line= 2
     2079164.226      373979.112      2079192.04      374500.142
#Sta/Elev= 30
       0 2841.13      10 2838.23    30.1 2833.09    40.1 2830.35    80.3 2817.81
    90.3 2815.01   100.3 2812.68   130.4 2807.15   160.6 2802.54   180.6 2800.28
   190.6 2798.23   200.7 2794.46   210.7 2789.61   220.8 2785.34   230.8 2782.98
   245.5 2782.63   250.8 2782.61   260.5 2782.76   270.9 2783.58     281    2785
     291 2786.66   341.2 2795.52   371.3 2801.57   381.3 2803.99   411.4 2812.02
   441.5 2819.76   461.6  2825.3   491.7 2834.38   511.7 2840.91   521.8 2844.41
#Mann= 3 , 0 , 0
       0      .1       0   245.5    .045       0   260.5      .1       0
Bank Sta=245.5,260.5
XS Rating Curve= 0 ,0
Exp/Cntr=0.3,0.1

Type RM Length L Ch R = 1 ,5831.2  ,537.1,553.1,569.1
XS GIS Cut Line= 3
     2078937.086      373811.886     2078949.064      374425.708
     2078945.416       374604.85
#Sta/Elev= 30
       0  2870.2    40.3 2855.19    60.4 2848.65    70.4  2845.9   181.2 2820.49
   211.4 2814.75   281.8 2804.82   322.1  2800.2   382.4 2795.98   412.6 2794.37
   432.8 2793.82     473 2793.92   483.1 2793.25   493.2 2791.52   523.6  2784.2
   538.6 2782.87   553.6 2782.63   573.7 2783.64   583.8 2785.41   593.8 2788.37
   603.9 2793.06   613.9 2800.17   633.8 2817.83   643.8 2825.81   673.7 2846.78
   703.5 2866.19   723.4 2877.26   773.2 2901.39   783.2 2905.32   793.1 2907.29
#Mann= 3 , 0 , 0
       0      .1       0   523.6    .045       0   538.6      .1       0
Bank Sta=523.6,538.6
XS Rating Curve= 0 ,0
Exp/Cntr=0.3,0.1

Type RM Length L Ch R = 1 ,5278.1  ,405.4,407.7,410
XS GIS Cut Line= 2
     2078824.666      373753.638     2078339.817      374292.555
#Sta/Elev= 30
       0 2876.41    30.2 2863.54    70.5 2846.83    80.6  2843.4   130.9  2827.3
     141 2823.75     151  2819.7   211.4  2792.3   221.5 2787.79   231.6 2783.69
   241.6 2781.68   251.7 2781.04   352.4  2779.9   412.8 2776.94   461.4 2775.24
   476.4 2775.08   483.3 2775.07   493.4 2775.11   503.4 2775.98   513.5 2778.72
   523.6 2783.91   533.6  2788.3   543.7 2791.45   563.8 2793.74   573.9 2795.48
   614.2  2804.7   634.3 2810.01   674.6  2821.4   704.8 2830.43   724.9 2837.16
#Mann= 3 , 0 , 0
       0      .1       0   461.4    .045       0   476.4      .1       0
Bank Sta=461.4,476.4
XS Rating Curve= 0 ,0
Exp/Cntr=0.3,0.1

Type RM Length L Ch R = 1 ,4870.4  ,427.6,422.6,417.9
XS GIS Cut Line= 2
     2078520.007      373580.254     2077993.116      374069.511
#Sta/Elev= 30
       0 2876.47      30 2864.29      40  2860.1    79.9 2842.78   119.8 2826.46
   129.8  2820.9   139.8 2814.28   189.7 2779.67   199.7 2773.16   209.7 2768.57
   219.7 2766.73   225.4 2766.63   229.7 2766.55   240.4 2766.56   259.6 2766.79
   279.6 2767.28   309.6 2767.83   369.5 2768.62   449.4 2769.25   499.3 2769.77
   509.3 2769.96   519.3 2770.74   529.3  2772.6   539.3 2774.99   589.2  2788.7
   659.1 2808.62   669.1 2811.37     699 2819.15     709 2821.99     719 2824.99
#Mann= 3 , 0 , 0
       0      .1       0   225.4    .045       0   240.4      .1       0
Bank Sta=225.4,240.4
XS Rating Curve= 0 ,0
Exp/Cntr=0.3,0.1

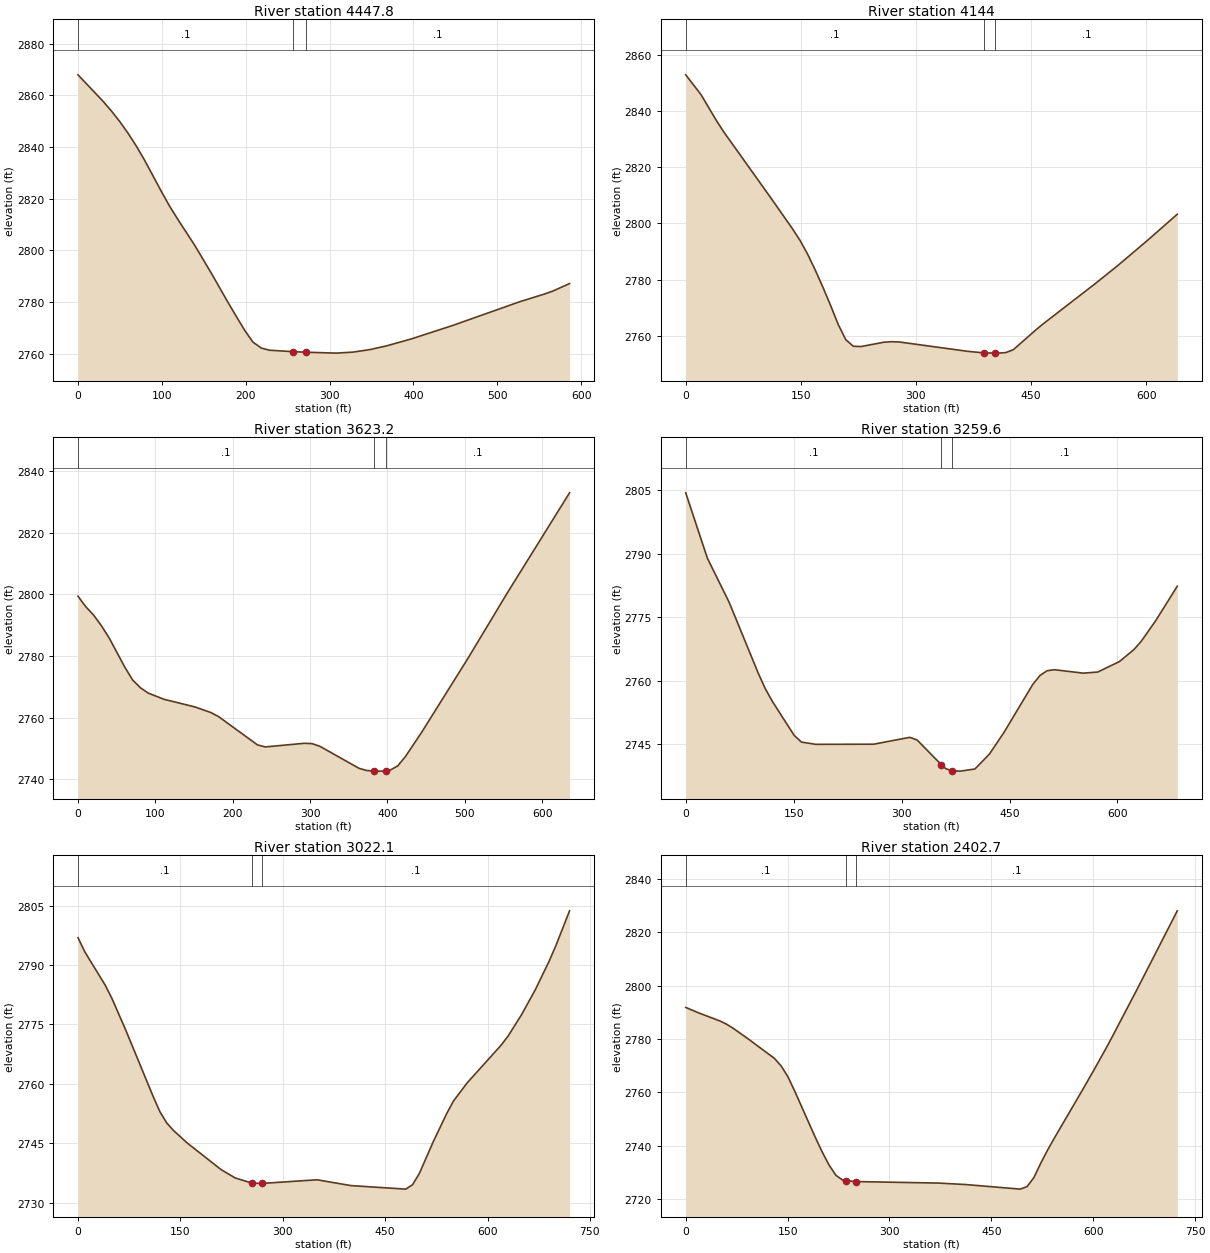
Type RM Length L Ch R = 1 ,4447.8  ,305.2,303.8,302.3
XS GIS Cut Line= 2
     2078135.784      373304.677     2077827.262      373803.051
#Sta/Elev= 30
       0 2867.92    29.8 2857.71    39.7 2853.99    49.7 2849.89    59.6 2845.36
    69.5  2840.4    79.5 2834.84    99.4  2822.8   109.3 2817.07   119.2 2811.92
   139.1 2802.01     159 2791.17   178.8 2779.92   188.8 2774.43   198.7 2769.12
   208.6 2764.52   218.6 2762.21   228.5 2761.38   256.9 2760.82   271.9 2760.61
     308 2760.26   327.8 2760.65   347.7  2761.6   367.6 2763.04   397.4 2765.75
   447.1    2771   526.5 2780.12   556.3 2783.13   566.3 2784.28   586.1 2787.18
#Mann= 3 , 0 , 0
       0      .1       0   256.9    .045       0   271.9      .1       0
Bank Sta=256.9,271.9
XS Rating Curve= 0 ,0
Exp/Cntr=0.3,0.1

Type RM Length L Ch R = 1 ,4144    ,509.2,520.8,532.6
XS GIS Cut Line= 3
     2077916.849      373109.284     2077697.251      373463.999
     2077588.315      373659.106
#Sta/Elev= 30
       0 2852.82    19.9  2845.8    39.7 2836.68    49.7 2832.48   109.3  2809.7
   139.1 2798.11     149 2793.95   158.9 2789.06   168.9 2783.37   178.8 2777.32
   188.7 2770.92   198.7 2764.11   208.6 2758.68   218.5 2756.35   228.5 2756.25
   258.3 2757.79   268.2 2757.97   278.1 2757.88   367.5 2754.55   388.6 2753.99
   403.6 2753.92   407.3 2753.91   417.2 2754.11   426.9 2755.12     456  2762.1
   465.8 2764.31   533.8 2778.64   562.9    2785   601.8 2793.99   640.6 2803.28
#Mann= 3 , 0 , 0
       0      .1       0   388.6    .045       0   403.6      .1       0
Bank Sta=388.6,403.6
XS Rating Curve= 0 ,0
Exp/Cntr=0.3,0.1

Type RM Length L Ch R = 1 ,3623.2  ,356.9,363.6,370.4
XS GIS Cut Line= 2
     2077662.338      372951.765     2077102.907      373253.126
#Sta/Elev= 30
       0 2799.39    10.1 2795.98    20.2 2793.26    30.3  2789.8    40.4 2785.81
    60.5 2776.39    70.6 2772.24    80.7  2769.7    90.8 2767.98     111 2765.98
   151.3 2763.48   171.5  2761.7   181.6 2760.38     232 2751.18   242.1 2750.53
   292.5  2751.7   302.6 2751.59   312.7 2750.73   363.1 2743.61   373.2 2742.88
   383.2  2742.7   393.4 2742.68   398.2 2742.82   403.4 2742.98   413.5 2744.41
   423.6 2747.54   443.8  2755.1   504.3 2779.34   554.8 2800.39   635.4  2832.9
#Mann= 3 , 0 , 0
       0      .1       0   383.2    .045       0   398.2      .1       0
Bank Sta=383.2,398.2
XS Rating Curve= 0 ,0
Exp/Cntr=0.3,0.1

Type RM Length L Ch R = 1 ,3259.6  ,244.6,237.5,230.4
XS GIS Cut Line= 2
     2077624.222       372701.74     2076955.807      372843.046
#Sta/Elev= 30
       0 2804.34    30.1 2788.92    60.3 2778.54   100.5 2761.91   110.5 2758.16
   120.6 2755.09   150.7 2747.13   160.8 2745.54   180.8 2745.01   261.2 2745.04
   311.4 2746.66   321.5 2746.05   355.3  2740.2   361.7 2739.24   370.3 2738.78
   381.8 2738.69   401.9 2739.19     422 2742.69   442.1 2747.76   482.2 2759.11
   492.3 2761.24   502.3 2762.38   512.4 2762.61   552.6  2761.8   572.7 2762.07
   602.8 2764.54   622.9 2767.36     633  2769.3     653 2774.13   683.2 2782.31
#Mann= 3 , 0 , 0
       0      .1       0   355.3    .045       0   370.3      .1       0
Bank Sta=355.3,370.3
XS Rating Curve= 0 ,0
Exp/Cntr=0.3,0.1

Type RM Length L Ch R = 1 ,3022.1  ,629.5,619.4,609.3
XS GIS Cut Line= 2
     2077477.817      372412.881     2076849.019      372764.064
#Sta/Elev= 30
       0 2796.91      10 2793.34      40 2784.89      50 2781.46      70 2773.56
     110 2756.86     120 2752.96     130 2750.12     140  2748.2     160 2745.06
   210.1 2738.28   230.1 2736.24     255 2734.91     270 2734.84   350.1 2735.76
   400.1 2734.29   480.2  2733.4   490.2 2734.52   500.2 2737.38   520.2 2745.27
   540.2 2752.48   550.2 2755.68   570.2 2760.24   620.2 2769.82   630.2 2772.08
   650.2 2777.56   670.2 2783.84   690.2 2790.94   700.2 2794.93   720.2  2803.7
#Mann= 3 , 0 , 0
       0      .1       0     255    .045       0     270      .1       0
Bank Sta=255,270
XS Rating Curve= 0 ,0
Exp/Cntr=0.3,0.1

Type RM Length L Ch R = 1 ,2402.7  ,346.7,351,355.2
XS GIS Cut Line= 2
     2077022.017      371939.995     2076612.028      372536.481
#Sta/Elev= 30
       0 2791.78    20.1 2789.63    50.3 2786.71    60.3 2785.47    70.4 2783.87
    90.5 2780.26   130.7 2772.66   140.7 2769.79   150.8 2765.64   160.8 2760.23
     191 2742.95   201.1 2737.52   211.1 2732.66   221.2 2728.83   231.2 2727.02
   235.9 2726.81   250.9 2726.49     372 2725.93   412.2 2725.38   492.6 2723.66
   502.6 2724.61   512.7 2728.02   522.7 2733.35   532.8  2738.3   542.8 2742.81
   583.1 2760.35   603.2 2769.28   623.3  2778.5   663.5 2798.04   723.8    2828
#Mann= 3 , 0 , 0
       0      .1       0   235.9    .045       0   250.9      .1       0
Bank Sta=235.9,250.9
XS Rating Curve= 0 ,0
Exp/Cntr=0.3,0.1

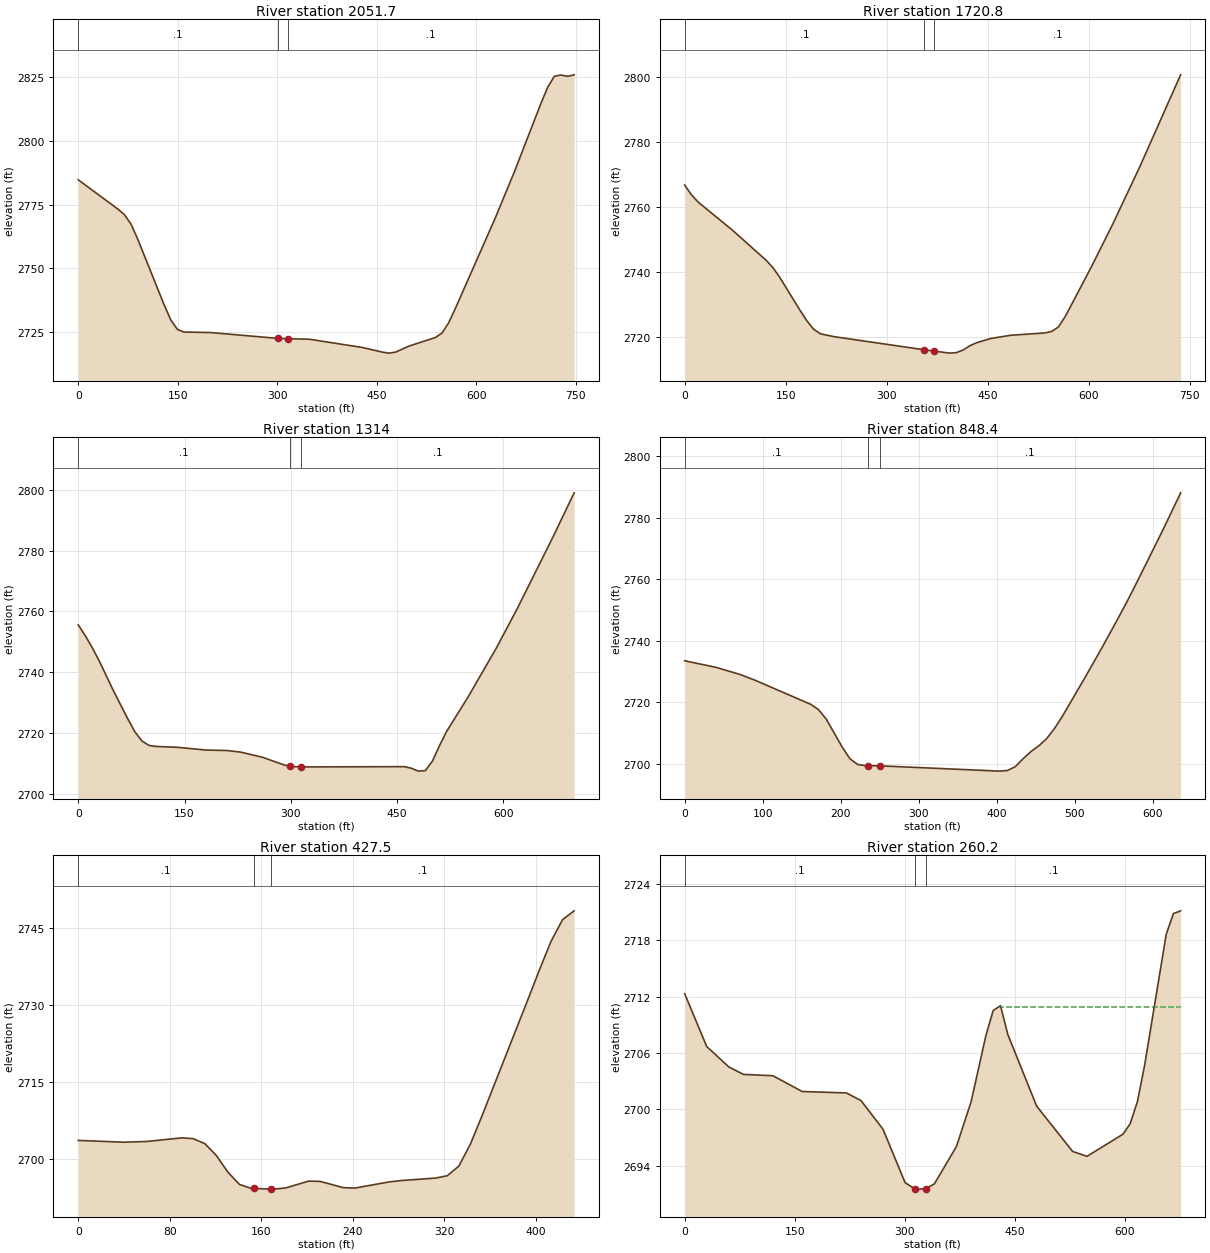
Type RM Length L Ch R = 1 ,2051.7  ,338.5,330.9,323.3
XS GIS Cut Line= 2
     2076813.262      371740.379     2076278.888      372263.511
#Sta/Elev= 30
       0 2784.73    59.8 2773.27    69.8 2771.06    79.8  2767.3    89.7  2761.5
   129.6 2735.74   139.6 2729.81   149.6 2726.14   159.5 2725.09   199.4  2724.9
   300.6 2722.61   315.6  2722.5     349 2722.26   428.8 2719.03   458.7 2717.22
   468.6 2716.83   478.6 2717.23   498.5 2719.57   538.4 2722.93   548.4 2724.66
   558.4 2728.62   568.3  2734.1   628.2 2769.37   658.1 2788.11     698 2814.84
   707.9 2820.95   717.9 2825.27   727.9 2825.77   737.8 2825.27   747.8 2825.85
#Mann= 3 , 0 , 0
       0      .1       0   300.6    .045       0   315.6      .1       0
Bank Sta=300.6,315.6
XS Rating Curve= 0 ,0
Exp/Cntr=0.3,0.1

Type RM Length L Ch R = 1 ,1720.8  ,413.8,406.8,399.9
XS GIS Cut Line= 2
     2076500.799      371436.919      2076169.36      372094.699
#Sta/Elev= 30
       0 2766.79    10.1 2763.79    20.2 2761.53    70.6 2752.98   121.1 2743.64
   131.2 2741.36   141.3 2738.37   171.5 2728.21   181.6 2724.99   191.7 2722.41
   201.8 2721.02     222 2720.14   355.6 2716.12   370.6 2715.71   393.5 2715.08
   403.6 2715.24   413.7 2716.05   423.8 2717.38   433.9  2718.3     454 2719.56
   484.3 2720.58   534.8 2721.29   544.9 2721.73     555 2723.12     565 2726.26
   575.1 2730.21   605.4 2742.18   635.7 2754.74     676 2772.45   736.6 2800.73
#Mann= 3 , 0 , 0
       0      .1       0   355.6    .045       0   370.6      .1       0
Bank Sta=355.6,370.6
XS Rating Curve= 0 ,0
Exp/Cntr=0.3,0.1

Type RM Length L Ch R = 1 ,1314    ,478.9,465.6,452.4
XS GIS Cut Line= 2
     2076012.925       371302.47     2075899.581      371992.884
#Sta/Elev= 30
       0 2755.58      10 2752.01      20 2747.98      30 2743.53      50 2733.76
      70 2724.63      80 2720.39      90 2717.35     100 2715.92     110 2715.58
   139.9 2715.31   179.9  2714.4   209.9 2714.25   229.9 2713.69   259.9 2712.03
   289.9 2709.55     299 2709.04     314 2708.85   459.8 2708.94   469.8 2708.44
   479.8 2707.47   489.8 2707.64   499.8  2710.8   509.8 2715.87   519.7  2720.5
   549.7 2731.71   589.7 2747.83   619.7 2761.03   669.7 2784.39   699.7 2798.97
#Mann= 3 , 0 , 0
       0      .1       0     299    .045       0     314      .1       0
Bank Sta=299,314
XS Rating Curve= 0 ,0
Exp/Cntr=0.3,0.1

Type RM Length L Ch R = 1 ,848.4   ,414.7,420.8,426.9
XS GIS Cut Line= 2
      2075424.32      371449.766     2075684.728      372029.679
#Sta/Elev= 30
       0 2733.55    40.4 2731.39    70.6 2729.13    90.8 2727.16   161.4 2719.41
   171.5 2717.69   181.6 2714.55   201.8 2705.55   211.9  2701.7     222 2699.82
   232.1 2699.47   235.1 2699.47   250.1 2699.41   403.6 2697.69   413.7  2697.9
   423.8 2699.14   433.9 2701.75     444 2704.08   454.1 2705.95   464.2 2708.31
   474.2  2711.6   484.3 2715.57   514.6 2728.74   534.8 2737.76     555 2747.07
   565.1 2751.85   575.2 2756.81   605.4 2772.17   615.5 2777.36   635.7 2788.11
#Mann= 3 , 0 , 0
       0      .1       0   235.1    .045       0   250.1      .1       0
Bank Sta=235.1,250.1
XS Rating Curve= 0 ,0
Exp/Cntr=0.3,0.1

Type RM Length L Ch R = 1 ,427.5   ,153.3,167.4,181.4
XS GIS Cut Line= 3
     2075177.848      371736.532     2075167.976      371846.774
      2075227.21      372164.338
#Sta/Elev= 30
       0 2703.56    40.2 2703.21    60.4 2703.36    90.6 2704.06   100.6  2703.9
   110.7 2702.94   120.8 2700.62   130.9 2697.36     141 2694.97   151.1 2694.21
   153.4 2694.18   168.4 2694.06   171.2 2694.05   181.4 2694.28   201.5 2695.61
   211.6 2695.56   231.8 2694.34   241.9 2694.25   272.2 2695.47   282.3 2695.72
   312.6 2696.21   322.7 2696.66   332.8 2698.53   342.9  2702.8     353 2708.29
   393.3 2731.08   403.4 2736.88   413.5 2742.43   423.6 2746.67   433.7 2748.38
#Mann= 3 , 0 , 0
       0      .1       0   153.4    .045       0   168.4      .1       0
Bank Sta=153.4,168.4
XS Rating Curve= 0 ,0
Exp/Cntr=0.3,0.1

Type RM Length L Ch R = 1 ,260.2   ,124.7,118.6,112.4
XS GIS Cut Line= 3
     2075157.268      371577.933     2074974.504      371978.771
     2075024.825      372208.764
#Sta/Elev= 30
       0  2712.3      30 2706.68    60.1 2704.51    80.1 2703.71   120.2 2703.57
   160.2 2701.89   220.3 2701.74   240.3 2700.93   270.3 2697.88   300.4  2692.2
   313.9 2691.51   320.4  2691.5   328.9 2691.56   340.4 2692.06   370.4 2696.03
   390.5 2700.82   410.5 2707.81   420.5 2710.51   430.5 2711.02   440.5 2707.95
   479.8 2700.33   528.8 2695.51   548.4 2694.99   597.5 2697.35   607.3 2698.47
   617.1 2700.81   626.9 2704.66   656.4 2718.63   666.2 2720.83     676 2721.12
#Mann= 3 , 0 , 0
       0      .1       0   313.9    .045       0   328.9      .1       0
#XS Ineff= 2 , 0
                          426.97         2710.89
Permanent Ineff=
       F       F
Bank Sta=313.9,328.9
XS Rating Curve= 0 ,0
Exp/Cntr=0.3,0.1

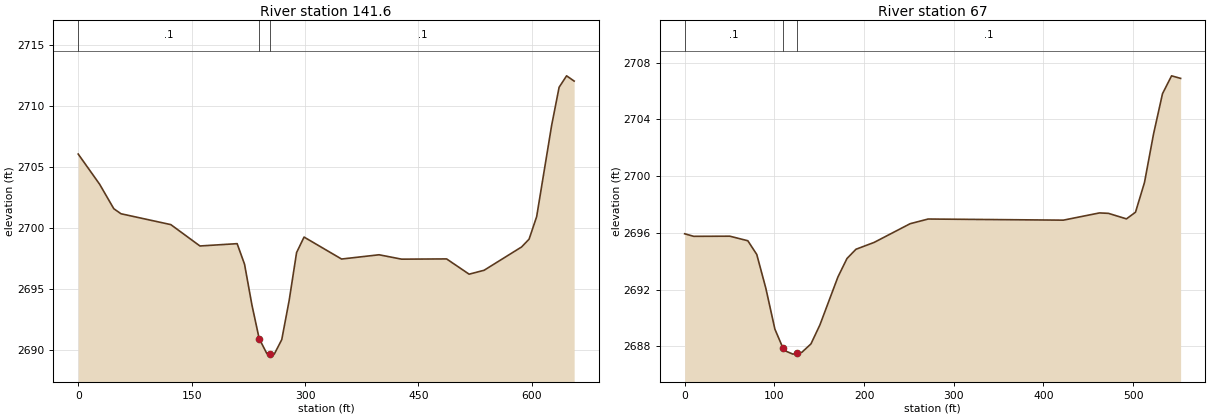
Type RM Length L Ch R = 1 ,141.6   ,74.2,74.6,74.9
XS GIS Cut Line= 4
      2074929.55       371571.38      2074935.18      371712.641
     2074912.232      371858.277     2074973.783      372220.132
#Sta/Elev= 30
       0 2706.05    28.3 2703.58    47.1 2701.57    56.6 2701.16   122.5 2700.27
     161 2698.52   210.2 2698.71     220 2697.02   229.8 2693.67   239.3 2690.94
   249.5  2689.7   254.3 2689.68   259.3 2689.66   269.2 2690.85     279 2694.06
   288.8 2697.98   298.7 2699.25   348.3 2697.45   397.9  2697.8   427.7 2697.44
   487.2 2697.46     517 2696.21   536.8 2696.53   586.4 2698.44   596.3 2699.08
   606.3 2700.92   626.1 2708.39     636 2711.52   645.9 2712.46   655.9 2712.03
#Mann= 3 , 0 , 0
       0      .1       0   239.3    .045       0   254.3      .1       0
#XS Ineff= 2 , 0
                          299.39         2699.14
Permanent Ineff=
       F       F
Bank Sta=239.3,254.3
XS Rating Curve= 0 ,0
Exp/Cntr=0.3,0.1

Type RM Length L Ch R = 1 ,67      ,65.5,67,68.5
XS GIS Cut Line= 3
     2074866.423      371683.516     2074837.155      371851.932
     2074932.826      372221.771
#Sta/Elev= 30
       0 2695.94    10.1 2695.76    50.3 2695.77    70.4 2695.45    80.4 2694.48
    90.5  2692.1   100.6 2689.22   109.7 2687.87   110.6 2687.73   120.7 2687.46
   124.7 2687.51   130.7 2687.59   140.8 2688.18   150.8 2689.52   170.9  2692.9
     181  2694.2     191 2694.85   211.2 2695.33   251.4 2696.65   271.5 2696.98
   422.3  2696.9   462.5 2697.41   472.5 2697.38   492.6 2696.99   502.7 2697.46
   512.7 2699.55   522.8 2702.97   532.8 2705.81   542.9 2707.07     553 2706.89
#Mann= 3 , 0 , 0
       0      .1       0   109.7    .045       0   124.7      .1       0
Bank Sta=109.7,124.7
XS Rating Curve= 0 ,0
Exp/Cntr=0.3,0.1

Chan Stop Cuts=-1
Use User Specified Reach Order=0